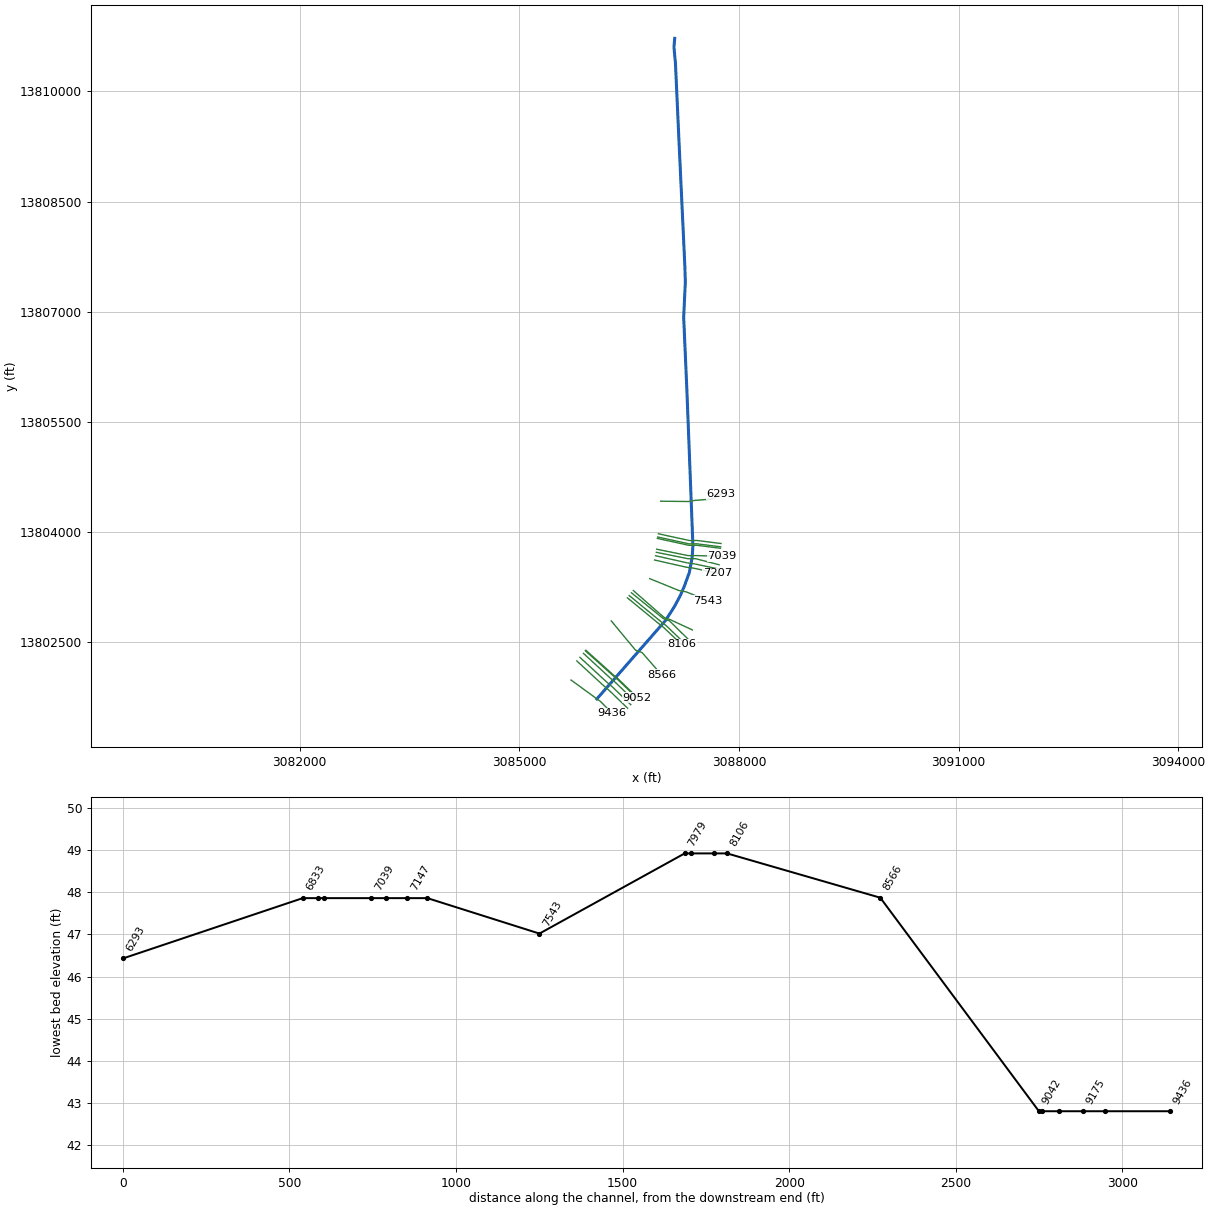
--- D139-00-00.prj (project) ---

Proj Title=D139-00-00
Current Plan=p06
Default Exp/Contr=.3,.1
English Units
Geom File=g01
Flow File=f06
Flow File=f05
Flow File=f04
Plan File=p02
Plan File=p06
Plan File=p01
Y Axis Title=Elevation
X Axis Title(PF)=Main Channel Distance
X Axis Title(XS)=Station
BEGIN DESCRIPTION:
Brays Bayou Watershed
Chimney Rock Diversion Channel
HCFCD Unit D139-00-00
Flood Hazard & Floodway Model
10, 2, 1, 0.2% Event
Filename D139.prj
Prepared by: Dodson & Associates, Inc.   Date: September 2003
Reviewed by:____________________	 Date:_________
STATUS (Final RAS, SVSQ)
END DESCRIPTION:
DSS File=dss
DSS Export Rating Curves= 0
DSS Export Rating Curve Sorted= 0
DSS Export Volume Flow Curves= 0
DXF Filename=e:\1109 Brays\D139\PFPlot.dxf
DXF OffsetX= 0
DXF OffsetY= 0
DXF ScaleX= 1
DXF ScaleY= 10

--- D139-00-00.p06 (plan) ---

Plan Title=Floodway
Version=Version 3.0.1  Mar 2001
Short Identifier=Floodway
Geom File=g01
Flow File=f06
Subcritical Flow
K Sum by GR= 0
Std Step Tol= 0.01
Critical Tol= 0.01
Num of Std Step Trials= 20
Max Error Tol= 0.3
Flow Tol Ratio= 0.001
Split Flow NTrial= 30
Split Flow Tol= 0.02
Split Flow Ratio= 0.02
Log Output Level= 0
Friction Slope Method= 1
Unsteady Friction Slope Method= 2
Parabolic Critical Depth
Global Vel Dist= 0 , 0 , 0
Global Log Level= 0
CheckData=True
Encroach Param=-1 ,0,0, 2
Encroach River=D139-00-00
Encroach Reach=Reach 0
Encroach Node=9436
       1  406.18  462.12
Encroach Node=9240
       1  517.76  580.03
Encroach Node=9175
       1  517.76  580.03
Encroach Node=9146
       1  517.76  580.03
Encroach Node=9102
       1  517.76  580.03
Encroach Node=9052
       1  520.76  583.03
Encroach Node=9042
       1  520.76  583.03
Encroach Node=8566
       1  532.62  597.77
Encroach Node=8106
       1  570.74  623.14
Encroach Node=8066
       1  563.74  616.14
Encroach Node=8044
       1  563.74  626.14
Encroach Node=7998
       1  573.74  626.14
Encroach Node=7979
       1  570.74  623.14
Encroach Node=7543
       1  447.13  533.14
Encroach Node=7207
       1  456.74  527.67
Encroach Node=7147
       1  454.74  525.67
Encroach Node=7123
       1  453.74  525.67
Encroach Node=7081
       1  453.74  524.67
Encroach Node=7039
       1  454.74  525.67
Encroach Node=6897
       1  458.74  529.67
Encroach Node=6877
       1  456.74  527.67
Encroach Node=6833
       1  446.74  517.67
Encroach Node=6563
       1  376.51  517.67
Encroach Node=6293
       1  376.51  452.11
Encroach Node=6247
       1  384.52  459.77
Encroach Node=6196
       1  386.52  462.45
Encroach Node=5552
       1   377.1  465.02
Encroach Node=5512
       1  380.34  465.32
Encroach Node=5490
       1  379.44  465.32
Encroach Node=5470
       1  379.44  463.38
Encroach Node=5429
       1  380.34  467.02
Encroach Node=4556
       1  339.21  420.66
Encroach Node=4082
       1  377.17  454.41
Encroach Node=4017
       1  377.17  454.41
Encroach Node=3972
       1  369.73  454.41
Encroach Node=3927
       1  369.73  451.41
Encroach Node=3860
       1  371.17  448.58
Encroach Node=3523
       1  238.99  316.94
Encroach Node=3204
       1  372.56  445.14
Encroach Node=3174
       1  366.67  442.14
Encroach Node=3148
       1  366.67  442.14
Encroach Node=3122
       1  366.89  441.89
Encroach Node=3106
       1  367.56  440.14
Encroach Node=2800
       1  398.56  475.65
Encroach Node=2743
       1  399.56  488.28
Encroach Node=2723
       1  397.56   473.9
Encroach Node=2697
       1  397.56   473.9
Encroach Node=2671
       1  397.56  474.65
Encroach Node=2628
       1  398.56  475.65
Encroach Node=2025
       1  374.54  447.63
Encroach Node=1605
       1  1022.5 1105.34
Encroach Node=1535
       1 1036.56 1109.34
Encroach Node=1507
       1 1036.56 1109.34
Encroach Node=1479
       1 1034.23 1111.34
Encroach Node=1414
       1 1038.56 1111.34
Encroach Node=521
       1  459.18  525.97
Encroach Node=335
       1  443.18  509.97
Encroach Node=325
       1  439.18  505.97
Encroach Node=289
       1  424.18  490.97
Encroach Node=203
       1  284.18  490.97
Encroach Node=114
       1  284.18  350.97
Encroach Node=94
       1  284.18  350.97
Encroach Reach=D139-00-00_0001
Encroach Node=9436
       1  406.18  462.12
Encroach Node=9240
       1  517.76  580.03
Encroach Node=9175
       1  517.76  580.03
Encroach Node=9146
       1  517.76  580.03
Encroach Node=9102
       1  517.76  580.03
Encroach Node=9052
       1  520.76  583.03
Encroach Node=9042
       1  520.76  583.03
Encroach Node=8566
       1  532.62  597.77
Encroach Node=8106
       1  570.74  623.14
Encroach Node=8066
       1  563.74  616.14
Encroach Node=8044
       1  563.74  626.14
Encroach Node=7998
       1  573.74  626.14
Encroach Node=7979
       1  570.74  623.14
Encroach Node=7543
       1  447.13  533.14
Encroach Node=7207
       1  456.74  527.67
Encroach Node=7147
       1  454.74  525.67
Encroach Node=7123
       1  453.74  525.67
Encroach Node=7081
       1  453.74  524.67
Encroach Node=7039
       1  454.74  525.67
Encroach Node=6897
       1  458.74  529.67
Encroach Node=6877
       1  456.74  527.67
Encroach Node=6833
       1  446.74  517.67
Encroach Node=6563
       1  376.51  517.67
Encroach Node=6293
       1  376.51  452.11
Encroach Node=6247
       1  384.52  459.77
Encroach Node=6196
       1  386.52  462.45
Encroach Node=5552
       1   377.1  465.02
Encroach Node=5512
       1  380.34  465.32
Encroach Node=5490
       1  379.44  465.32
Encroach Node=5470
       1  379.44  463.38
Encroach Node=5429
       1  380.34  467.02
Encroach Node=4556
       1  339.21  420.66
Encroach Node=4082
       1  377.17  454.41
Encroach Node=4017
       1  377.17  454.41
Encroach Node=3972
       1  369.73  454.41
Encroach Node=3927
       1  369.73  451.41
Encroach Node=3860
       1  371.17  448.58
Encroach Node=3523
       1  238.99  316.94
Encroach Node=3204
       1  372.56  445.14
Encroach Node=3174
       1  366.67  442.14
Encroach Node=3148
       1  366.67  442.14
Encroach Node=3122
       1  366.89  441.89
Encroach Node=3106
       1  367.56  440.14
Encroach Node=2800
       1  398.56  475.65
Encroach Node=2743
       1  399.56  488.28
Encroach Node=2723
       1  397.56   473.9
Encroach Node=2697
       1  397.56   473.9
Encroach Node=2671
       1  397.56  474.65
Encroach Node=2628
       1  398.56  475.65
Encroach Node=2025
       1  374.54  447.63
Encroach Node=1605
       1  1022.5 1105.34
Encroach Node=1535
       1 1036.56 1109.34
Encroach Node=1507
       1 1036.56 1109.34
Encroach Node=1479
       1 1034.23 1111.34
Encroach Node=1414
       1 1038.56 1111.34
Encroach Node=521
       1  459.18  525.97
Encroach Node=335
       1  443.18  509.97
Encroach Node=325
       1  439.18  505.97
Encroach Node=289
       1  424.18  490.97
Encroach Node=203
       1  284.18  490.97
Encroach Node=114
       1  284.18  350.97
Encroach Node=94
       1  284.18  350.97
Computation Interval=1HOUR
Output Interval=1HOUR
Run HTab= 0
Run UNet= 0
Run PostProcess= 0
UNET Theta= 1
UNET ZTol= 0.02
UNET ZSATol= 0.1
UNET MxIter= 20
UNET MaxInSteps= 20
UNET DtIC= 0
UNET DtMin= 0
UNET MaxCRTS= 20
UNET WFStab= 2
UNET SFStab= 1
UNET WFX= 1
UNET SFX= 1
UNET Convert EG Bridges=-1
UNET Use Existing IB Tables=-1
Instantaneous Interval=1HOUR
Write IC File= 0
Write Velocity= 0
Write Detailed= 0

--- D139-00-00.p01 (plan) ---

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Plan Title=Storage Routing
Short Identifier=Store_Rout
Geom File=g01
Flow File=f04
Encroach Param=-1 ,0,0, 0

--- D139-00-00.p02 (plan) ---

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Plan Title=FEMA Effective June 2007
Short Identifier=FEMAeff0607
Geom File=g01
Flow File=f05

--- D139-00-00.f06 (steady flow) ---

Flow Title=Floodway
Version=Version 3.0.1  Mar 2001
Number of Profiles= 2
Profile Names=1PCT_100yr,1PCTFloodway_100yrFW
River Rch & RM=D139-00-00,D139-00-00_0001 ,9436
      45      45
River Rch & RM=D139-00-00,D139-00-00_0001 ,9042
      82      82
River Rch & RM=D139-00-00,D139-00-00_0001 ,8566
     170     170
River Rch & RM=D139-00-00,D139-00-00_0001 ,7979
     293     293
River Rch & RM=D139-00-00,D139-00-00_0001 ,7543
     551     551
River Rch & RM=D139-00-00,D139-00-00_0001 ,7039
    1486    1486
River Rch & RM=D139-00-00,D139-00-00_0001 ,6247
    1173    1173
River Rch & RM=D139-00-00,D139-00-00_0001 ,5429
    1264    1264
River Rch & RM=D139-00-00,D139-00-00_0001 ,4556
    1342    1342
River Rch & RM=D139-00-00,D139-00-00_0001 ,3860
    1433    1433
River Rch & RM=D139-00-00,D139-00-00_0001 ,3106
    1493    1493
River Rch & RM=D139-00-00,D139-00-00_0001 ,2628
    1572    1572
River Rch & RM=D139-00-00,D139-00-00_0001 ,2025
    1657    1657
River Rch & RM=D139-00-00,D139-00-00_0001 ,1414
    1790    1790
River Rch & RM=D139-00-00,D139-00-00_0001 ,521
    1872    1872
Boundary for River Rch & Prof#=D139-00-00,D139-00-00_0001 , 1
Up Type= 0
Dn Type= 1
Dn Known WS=44.24
Boundary for River Rch & Prof#=D139-00-00,D139-00-00_0001 , 2
Up Type= 0
Dn Type= 1
Dn Known WS=44.24
DSS Import GetInterval= 0
DSS Import GetPeak= 0
DSS Import FillOption= 0

--- D139-00-00.f04 (steady flow) ---

Flow Title=Storage Routing
Version=Version 3.0.1  Mar 2001
Number of Profiles= 8
Profile Names=0.1,0.2,0.4,0.6,0.8,1.0,1.2,1.5
River Rch & RM=D139-00-00,D139-00-00_0001 ,9436
     109     218     436     654     872    1090    1308    1635
River Rch & RM=D139-00-00,D139-00-00_0001 ,6247
     188     376     752    1128    1504    1880    2256    2820
Boundary for River Rch & Prof#=D139-00-00,D139-00-00_0001 , 1
Up Type= 0
Dn Type= 3
Dn Slope=.001
Boundary for River Rch & Prof#=D139-00-00,D139-00-00_0001 , 2
Up Type= 0
Dn Type= 3
Dn Slope=.001
Boundary for River Rch & Prof#=D139-00-00,D139-00-00_0001 , 3
Up Type= 0
Dn Type= 3
Dn Slope=.001
Boundary for River Rch & Prof#=D139-00-00,D139-00-00_0001 , 4
Up Type= 0
Dn Type= 3
Dn Slope=.001
Boundary for River Rch & Prof#=D139-00-00,D139-00-00_0001 , 5
Up Type= 0
Dn Type= 3
Dn Slope=.001
Boundary for River Rch & Prof#=D139-00-00,D139-00-00_0001 , 6
Up Type= 0
Dn Type= 3
Dn Slope=.001
Boundary for River Rch & Prof#=D139-00-00,D139-00-00_0001 , 7
Up Type= 0
Dn Type= 3
Dn Slope=.001
Boundary for River Rch & Prof#=D139-00-00,D139-00-00_0001 , 8
Up Type= 0
Dn Type= 3
Dn Slope=.001
DSS Import GetInterval= 0
DSS Import GetPeak= 0
DSS Import FillOption= 0

--- D139-00-00.f05 (steady flow) ---

Flow Title=FEMA Effective June 2007
Version=Version 3.0.1  Mar 2001
Number of Profiles= 4
Profile Names=10PCT_10yr,2PCT_50yr,1PCT_100yr,0.2PCT_500yr
River Rch & RM=D139-00-00,D139-00-00_0001 ,9436
      29      38      45      61
River Rch & RM=D139-00-00,D139-00-00_0001 ,9042
      53      70      82     111
River Rch & RM=D139-00-00,D139-00-00_0001 ,8566
     110     147     170     230
River Rch & RM=D139-00-00,D139-00-00_0001 ,7979
     188     254     293     396
River Rch & RM=D139-00-00,D139-00-00_0001 ,7543
     351     480     551     740
River Rch & RM=D139-00-00,D139-00-00_0001 ,7039
     936    1300    1486    1981
River Rch & RM=D139-00-00,D139-00-00_0001 ,6247
     985    1064    1173    1665
River Rch & RM=D139-00-00,D139-00-00_0001 ,5429
    1040    1142    1264    1782
River Rch & RM=D139-00-00,D139-00-00_0001 ,4556
    1085    1209    1342    1882
River Rch & RM=D139-00-00,D139-00-00_0001 ,3860
    1137    1285    1433    1996
River Rch & RM=D139-00-00,D139-00-00_0001 ,3106
    1172    1336    1493    2072
River Rch & RM=D139-00-00,D139-00-00_0001 ,2628
    1216    1403    1572    2172
River Rch & RM=D139-00-00,D139-00-00_0001 ,2025
    1263    1475    1657    2278
River Rch & RM=D139-00-00,D139-00-00_0001 ,1414
    1335    1586    1790    2443
River Rch & RM=D139-00-00,D139-00-00_0001 ,521
    1379    1655    1872    2544
Boundary for River Rch & Prof#=D139-00-00,D139-00-00_0001 , 1
Up Type= 0
Dn Type= 3
Dn Slope=.001
Boundary for River Rch & Prof#=D139-00-00,D139-00-00_0001 , 2
Up Type= 0
Dn Type= 3
Dn Slope=.001
Boundary for River Rch & Prof#=D139-00-00,D139-00-00_0001 , 3
Up Type= 0
Dn Type= 3
Dn Slope=.001
Boundary for River Rch & Prof#=D139-00-00,D139-00-00_0001 , 4
Up Type= 0
Dn Type= 3
Dn Slope=.001
DSS Import GetInterval= 0
DSS Import GetPeak= 0
DSS Import FillOption= 0

--- D139-00-00.g01 (geometry) ---

Geom Title=D139-00-00 June 2007
Version=Version 3.0.1  Mar 2001

River Reach=D139-00-00      ,D139-00-00_0001
Reach XY= 30
      3086059.35    13801732.105     3086059.698      13801732.5
       3086092.5    13801769.864     3086999.325    13802802.813
     3087118.687    13802989.739     3087197.512    13803136.127
     3087258.319     13803278.01     3087321.378    13803451.423
     3087359.664    13803651.861     3087370.924    13803814.014
     3087366.794    13803921.794     3087366.766      13803922.5
     3087366.192      13803937.5     3087365.132    13803965.132
     3087361.257    13804066.257     3087359.867      13804102.5
     3087359.596    13804109.596     3087357.934    13804152.934
     3087354.059    13804254.059     3087353.543      13804267.5
     3087352.969      13804282.5     3087346.151    13804460.371
     3087287.596    13805955.776     3087244.806    13806926.438
     3087267.327    13807406.139     3087260.571    13807626.846
     3087183.999    13809252.874       3087132.2    13810385.688
     3087111.931    13810604.144     3087122.606    13810722.968

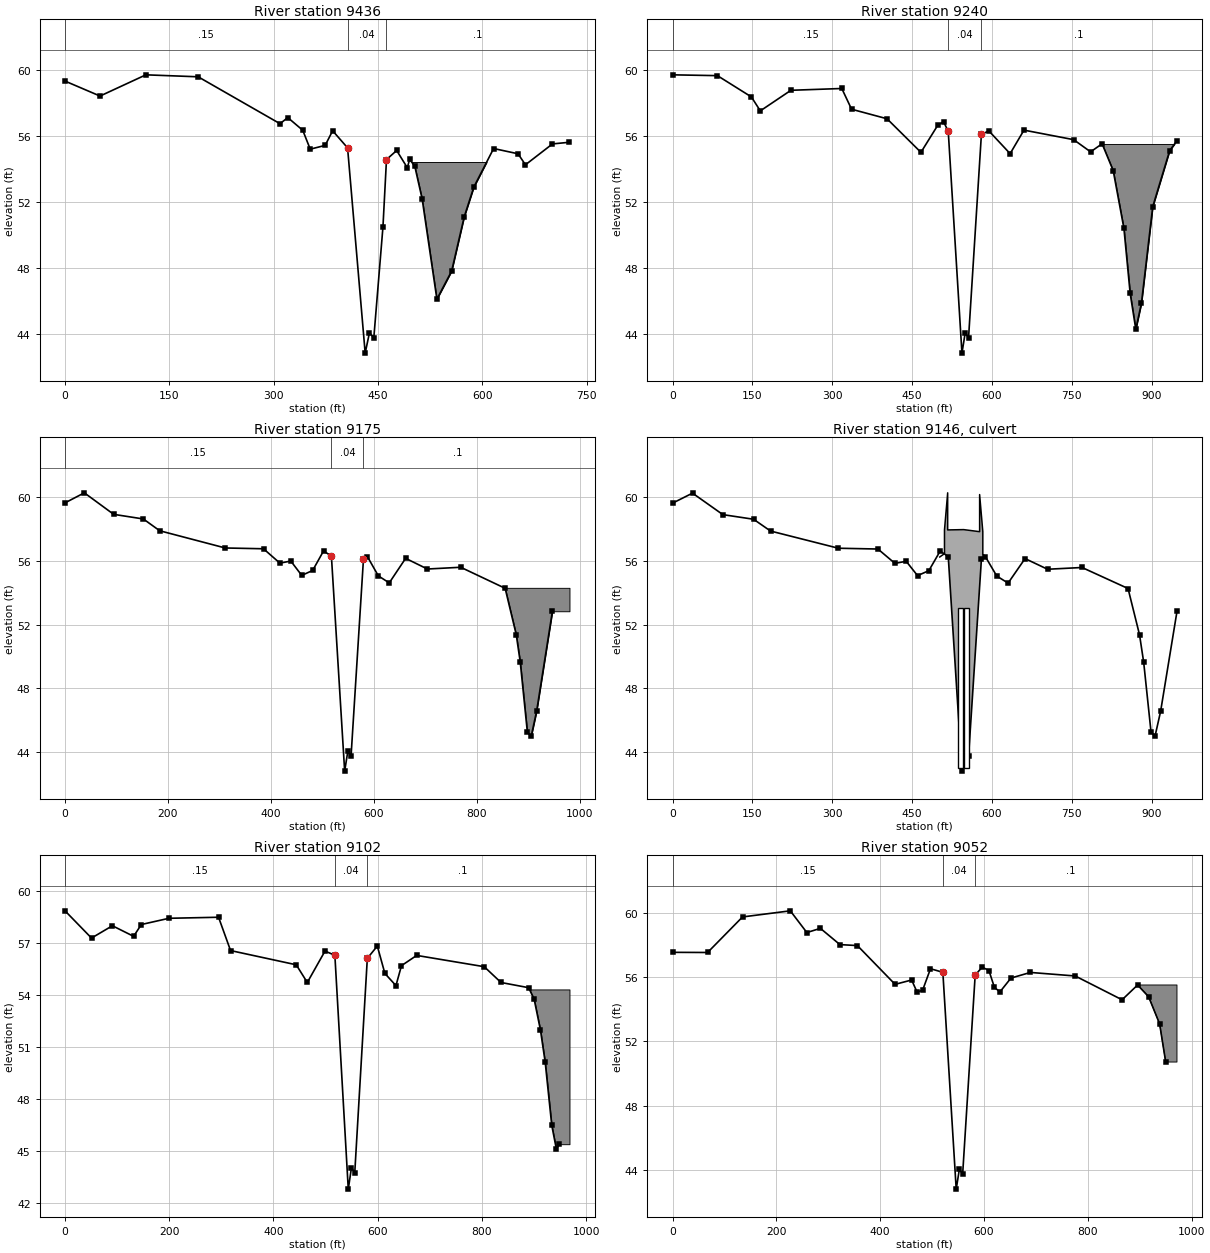
Type RM Length L Ch R = 1 ,9436    ,216.49,196.28,194.16
BEGIN DESCRIPTION:
Added Cross Section to Meet LODS
END DESCRIPTION:
XS GIS Cut Line= 3
      3085706.77    13801989.132      3086108.57    13801697.201
     3086269.733    13801535.195
#Sta/Elev= 30
       0   59.35   50.34   58.44  116.24   59.73  191.41   59.61  309.01   56.76
  320.27   57.13  341.75   56.36  352.49   55.21  373.97   55.44  384.71   56.33
  406.18   55.29  431.49   42.81  437.63   44.05  443.92   43.75  457.04   50.48
  462.12   54.58  476.79   55.13  492.09   54.08  495.33   54.59  502.76   54.18
  513.36   52.19  534.58   46.09  555.79    47.8  573.81   51.09  587.61    52.9
  616.13   55.25  651.25   54.93  661.86   54.26  700.76   55.53  725.17   55.63
#Mann= 3 , 0 , 0
       0     .15       0  406.18     .04       0  462.12      .1       0
#XS Ineff= 2 , 0
       0     319             722       0
Permanent Ineff=
       F       F
#Block Obstruct= 1 ,-1
     497  611.04   54.43
Bank Sta=406.18,462.12
XS Rating Curve= 0
Exp/Cntr=.3,.1

Type RM Length L Ch R = 1 ,9240    ,65.76,65.03,66.67
BEGIN DESCRIPTION:
Surveyed cross-section 9102/XS4
END DESCRIPTION:
XS GIS Cut Line= 4
     3085784.936     13802249.07      3086152.22     13801911.54
     3086228.808    13801846.635     3086479.179     13801604.82
#Sta/Elev= 30
       0   59.72   84.32   59.67  148.01   58.38  164.88   57.53  222.32   58.78
  317.87   58.89  336.23   57.63   402.8   57.05  466.49   55.01  498.34   56.67
  508.98   56.87  517.76   56.29  543.49   42.81  549.63   44.05  555.92   43.75
  580.03   56.11  594.12   56.31  633.95   54.93  659.96   56.36  753.26   55.78
  785.08   55.04  806.69   55.53  827.52    53.9  847.64   50.39  859.35   46.45
  869.95   44.26  880.56   45.85  901.78   51.71   933.6   55.12  947.29   55.72
#Mann= 3 , 0 , 0
       0     .15       0  517.76     .04       0  580.03      .1       0
#XS Ineff= 2 , 0
       0     441             923       0
Permanent Ineff=
       T       T
#Block Obstruct= 1 ,-1
  806.29  962.01   55.52
Bank Sta=517.76,580.03
XS Rating Curve= 0
Exp/Cntr=.5,.3

Type RM Length L Ch R = 1 ,9175    ,73.29,72.48,74.3
BEGIN DESCRIPTION:
Surveyed cross-section 9102/XS3
END DESCRIPTION:
XS GIS Cut Line= 4
     3085827.844     13802297.91     3086195.128     13801960.38
     3086271.716    13801895.475     3086522.087     13801653.66
#Sta/Elev= 30
       0   59.64   37.55   60.27    94.6   58.92  152.21   58.63  184.06   57.89
  311.45   56.81  385.76   56.76  417.61   55.86  438.84   55.99  460.08   55.09
  481.31    55.4  502.55   56.63  517.76   56.29  543.49   42.81  549.63   44.05
  555.92   43.75  580.03   56.11  587.69   56.27  608.94   55.06  630.16   54.62
  661.99   56.16  704.26   55.49  769.03    55.6   855.4   54.28  876.99   51.37
  884.76   49.65  898.58   45.26  905.97   44.99  916.58   46.57  947.29   52.84
#Mann= 3 , 0 , 0
       0     .15       0  517.76     .04       0  580.03      .1       0
#XS Ineff= 2 , 0
       0     437             871       0
Permanent Ineff=
       T       T
#Block Obstruct= 1 ,-1
  855.21  980.43   54.31
Bank Sta=517.76,580.03
XS Rating Curve= 0
Exp/Cntr=.5,.3

Type RM Length L Ch R = 2 ,9146    ,,,
BEGIN DESCRIPTION:
Burdine Culvert  Top-of-Road data is coded according to additional field measurement.
END DESCRIPTION:
Bridge Culvert--1,0,-1,-1, 0
Deck Dist Width WeirC Skew NumUp NumDn MinLoCord MaxHiCord MaxSubmerge Is_Ogee
12.24,48,2.6,0, 11, 11, , , .95, 0, 0,0,,
   501.8  510.69  510.69  516.69  516.69  546.69  576.69  576.69  582.69  582.69
  587.79
   56.26   56.47   57.96   60.29   57.96   57.98   57.85   60.18   57.85   56.43
   56.29
                                                                                
        
   501.8  510.69  510.69  516.69  516.69  546.69  576.69  576.69  582.69  582.69
  599.22
   56.26   56.47   57.96   60.29   57.96   57.98   57.85   60.18   57.85   56.43
   56.18
                                                                                
        
Multiple Barrel Culv=2,10,10,48,.014,.5,1,8,1,43.03,43, 2,Culvert #1  , 0 ,12.24
  541.19  541.19  552.19  552.19
Culvert Bottom n=.014
BC Design=,, 0 ,, 0 ,,,,,,

Type RM Length L Ch R = 1 ,9102    ,50.44,50.59,51.85
BEGIN DESCRIPTION:
Surveyed cross-sectionXS2
END DESCRIPTION:
XS GIS Cut Line= 4
     3085875.577    13802352.416     3086242.861    13802014.886
     3086319.449     13801949.98      3086569.82    13801708.166
#Sta/Elev= 30
       0   58.85   50.84   57.28   90.89   57.99  131.63   57.38  146.39   58.06
  199.47   58.42  294.61   58.48  317.62   56.56  443.64   55.74  464.87   54.72
  498.82   56.53  517.76   56.29  543.49   42.81  549.63   44.05  555.92   43.75
  580.03   56.11  599.21   56.82  613.73   55.24  634.95   54.54  645.56   55.69
  674.76   56.28  804.31   55.63  836.51   54.72  889.55   54.42  900.16   53.75
  912.27   51.97  921.37   50.11  933.86    46.5  942.59   45.14  947.29    45.4
#Mann= 3 , 0 , 0
       0     .15       0  517.76     .04       0  580.03      .1       0
#XS Ineff= 2 , 0
       0     434             814       0
Permanent Ineff=
       T       T
#Block Obstruct= 1 ,-1
  890.87   967.9   54.32
Bank Sta=517.76,580.03
XS Rating Curve= 0
Exp/Cntr=.5,.3

Type RM Length L Ch R = 1 ,9052    ,10.14,10.01,10.25
BEGIN DESCRIPTION:
Surveyed cross-section 9102/XS1
END DESCRIPTION:
XS GIS Cut Line= 4
      3085901.93     13802387.31     3086275.973     13802053.11
     3086352.561    13801988.205     3086602.932     13801746.39
#Sta/Elev= 30
       0   57.53   67.55   57.52  134.87   59.73   226.9   60.11  258.77   58.76
  284.88   59.02  322.51   58.01  356.13   57.95  428.75   55.54  460.62   55.81
  471.24   55.05  481.86   55.18  496.94   56.51  520.76   56.29  546.49   42.81
  552.63   44.05  558.92   43.75  583.03   56.11  596.49   56.61  609.51    56.4
  620.12   55.35  630.73   55.07  651.95   55.93  689.37   56.28  775.74   56.06
  866.05   54.58  895.94    55.5  917.15   54.77  938.37   53.08  950.07   50.71
#Mann= 3 , 0 , 0
       0     .15       0  520.76     .04       0  583.03      .1       0
#XS Ineff= 2 , 0
       0     436             782       0
Permanent Ineff=
       T       T
#Block Obstruct= 1 ,-1
  895.75  971.79    55.5
Bank Sta=520.76,583.03
XS Rating Curve= 0
Exp/Cntr=.3,.1

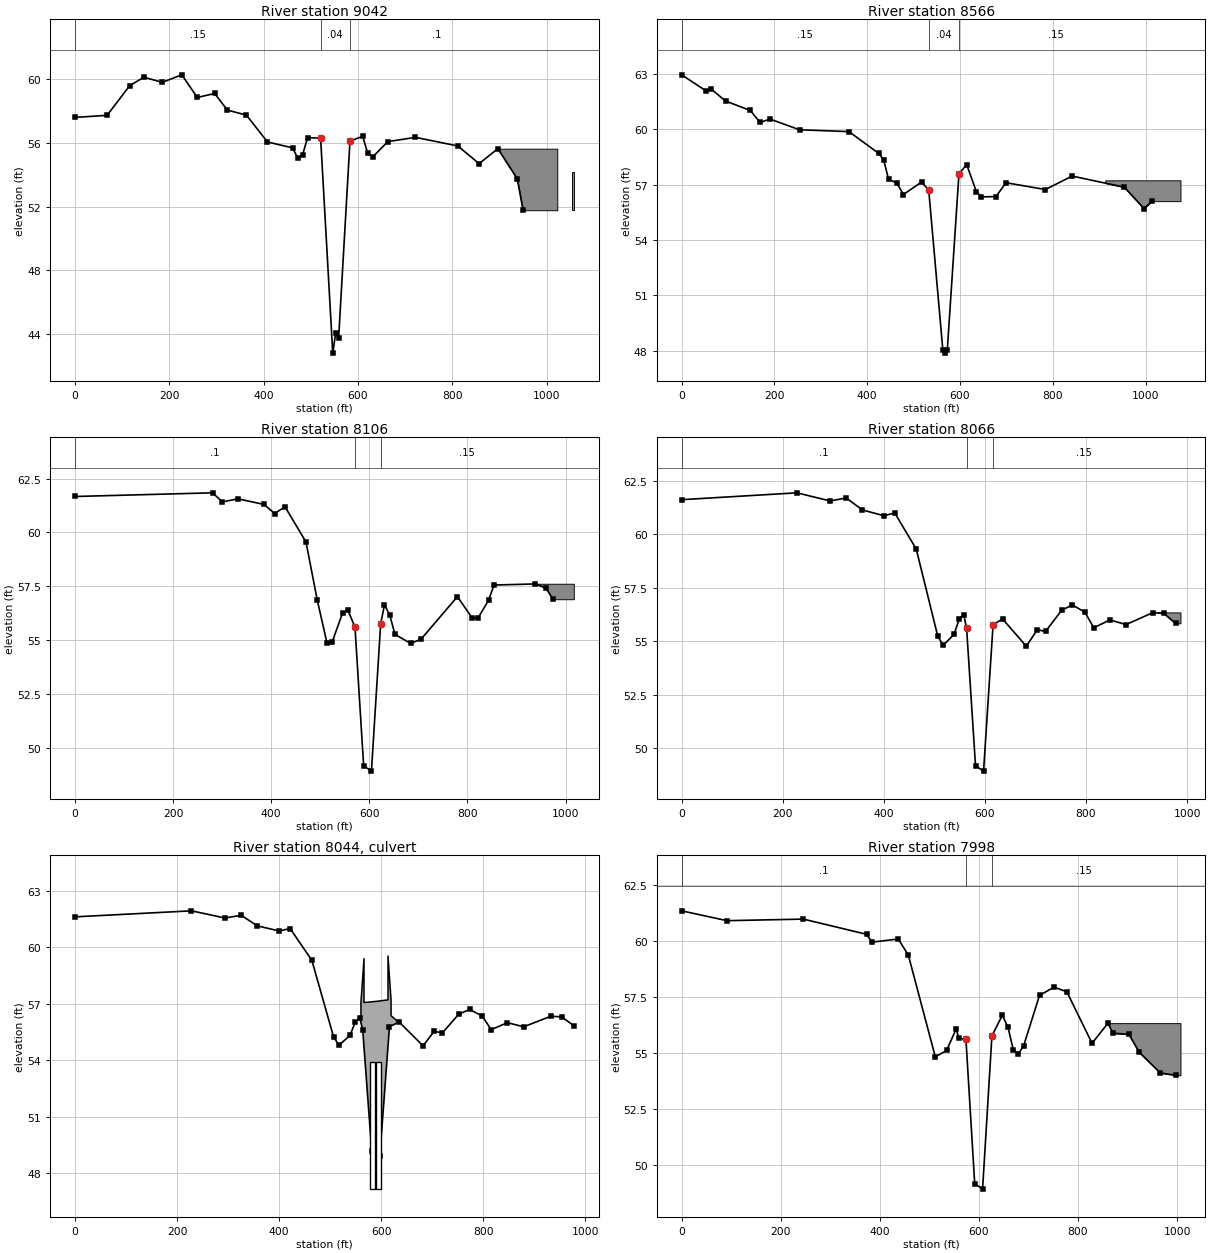
Type RM Length L Ch R = 1 ,9042    ,457.82,476.06,487.74
BEGIN DESCRIPTION:
Surveyed cross-section 9102
END DESCRIPTION:
XS GIS Cut Line= 4
      3085908.59     13802394.77      3086282.52     13802060.67
     3086359.108    13801995.765     3086609.479     13801753.95
#Sta/Elev= 30
       0   57.59   68.12   57.72  115.97   59.58  146.05   60.11  184.97   59.79
  226.51   60.26  259.34   58.84  296.08   59.09  323.08   58.05  363.62   57.73
  408.06   56.05  461.18   55.68  471.81   55.07  482.43   55.23  493.05   56.32
  520.76   56.29  546.49   42.81  552.63   44.05  558.92   43.75  583.03   56.11
  610.08    56.4  620.69   55.33   631.3   55.11  663.12   56.07  721.69   56.34
  811.64    55.8   856.8   54.69   896.5   55.63  937.61   53.74  949.92   51.77
#Mann= 3 , 0 , 0
       0     .15       0  520.76     .04       0  583.03      .1       0
#XS Ineff= 2 , 0
       0     436             776       0
Permanent Ineff=
       T       T
#Block Obstruct= 2 ,-1
  896.74  1022.5   55.63 1054.34 1057.52   54.19
Bank Sta=520.76,583.03
XS Rating Curve= 0
Exp/Cntr=.3,.1

Type RM Length L Ch R = 1 ,8566    ,478.8,459.85,455.59
BEGIN DESCRIPTION:
Surveyed cross-section
END DESCRIPTION:
XS GIS Cut Line= 4
     3086255.811    13802793.983     3086586.678    13802396.378
     3086677.537    13802361.889     3086941.254    13802061.729
#Sta/Elev= 30
       0   62.96   51.96    62.1   62.61   62.21   94.56   61.54  147.82   61.03
  169.12   60.38  190.57   60.56  254.33   59.98  360.84   59.88  424.74    58.7
  435.39   58.36  446.04   57.29  463.77    57.1     478   56.47  517.26   57.15
  532.62   56.71  563.03   48.04  567.89   47.87  572.63   48.03  597.77   57.59
  614.45   58.09  635.25   56.63  645.88   56.34  677.76   56.36  699.02   57.11
  784.05   56.74  841.66   57.47  954.11   56.87  996.62   55.71    1014   56.11
#Mann= 3 , 0 , 0
       0     .15       0  532.62     .04       0  597.77     .15       0
#XS Ineff= 2 , 0
       0     439             669       0
Permanent Ineff=
       T       T
#Block Obstruct= 1 ,-1
  913.17 1075.33   57.24
Bank Sta=532.62,597.77
XS Rating Curve= 0
Exp/Cntr=.3,.1

Type RM Length L Ch R = 1 ,8106    ,40.05,40.38,41.86
BEGIN DESCRIPTION:
Copied cross-section 7998/XS4
END DESCRIPTION:
XS GIS Cut Line= 4
      3086475.61     13803108.24     3086914.665     13802748.35
     3086971.309     13802704.52     3087214.678     13802474.55
#Sta/Elev= 30
       0   61.67  280.44   61.84  300.31   61.42  332.28   61.56  385.58    61.3
  406.89   60.88  428.21   61.19  470.84   59.56  493.79   56.87  513.48   54.89
  524.14   54.91  545.45   56.26  556.11    56.4  570.74   55.61   588.4   49.17
   604.3   48.92  623.14   55.77  630.92   56.64   641.6   56.17  652.21   55.27
  684.04   54.85  705.26   55.04  779.54   57.02  809.71   56.03  821.98   56.04
   843.2   56.86  854.22   57.56   938.7   57.61  959.92   57.42  974.16    56.9
#Mann= 3 , 0 , 0
       0      .1       0  570.74     .04       0  623.14     .15       0
#XS Ineff= 2 , 0
       0     443             710       0
Permanent Ineff=
       T       T
#Block Obstruct= 1 ,-1
  938.55 1016.79   57.62
Bank Sta=570.74,623.14
XS Rating Curve= 0
Exp/Cntr=.5,.3

Type RM Length L Ch R = 1 ,8066    ,52.16,67.23,78.03
BEGIN DESCRIPTION:
Copied cross-section 7998/XS3
END DESCRIPTION:
XS GIS Cut Line= 4
      3086500.97     13803139.17     3086938.762     13802780.32
      3087006.11     13802729.08     3087242.306     13802503.48
#Sta/Elev= 30
       0   61.61  228.26   61.93  293.61   61.55  325.58   61.69  357.56   61.13
  400.19   60.86  421.51   60.99  464.14    59.3  506.78   55.22  517.44    54.8
  538.75   55.31  549.41   56.04  557.97   56.24  563.74   55.61   581.4   49.17
   597.3   48.92  616.14   55.77  634.97   56.03  681.94   54.76  703.66   55.53
  719.99   55.45  751.82   56.44  773.03   56.69  797.82   56.35  815.47   55.62
   847.3   55.99  879.13   55.77  932.18   56.33  953.39    56.3  977.32   55.83
#Mann= 3 , 0 , 0
       0      .1       0  563.74     .04       0  616.14     .15       0
#XS Ineff= 2 , 0
       0     440             707       0
Permanent Ineff=
       T       T
#Block Obstruct= 1 ,-1
   943.1   986.9   56.34
Bank Sta=563.74,616.14
XS Rating Curve= 0
Exp/Cntr=.5,.3

Type RM Length L Ch R = 2 ,8044    ,,,
BEGIN DESCRIPTION:
McKnight Culvert.  Top-of-Road data is coded according to additional field measurement.
END DESCRIPTION:
Bridge Culvert--1,0,-1,-1, 0
Deck Dist Width WeirC Skew NumUp NumDn MinLoCord MaxHiCord MaxSubmerge Is_Ogee
14.615,38,2.6,0, 11, 11, , , .95, 0, 0,0,,
  557.98  560.29  560.29  566.29  566.29  589.79  613.29  613.29  619.29  619.29
  633.59
   56.23   56.12   57.06   59.39   57.06   57.12    57.2   59.53    57.2   56.36
   56.03
                                                                                
        
  553.95  569.78  569.78  575.78  575.78  599.28  622.78  622.78  628.78  628.78
  636.76
   56.04   56.12   57.06   59.39   57.06   57.12    57.2   59.53    57.2   56.36
   56.24
                                                                                
        
Multiple Barrel Culv=2,6.75,10,38,.014,.5,1,8,2,47.15,47.15, 2,Culvert #1  , 0 ,14.615
  583.79  590.28  594.79  601.28
Culvert Bottom n=.014
BC Design=,, 0 ,, 0 ,,,,,,

Type RM Length L Ch R = 1 ,7998    ,19.71,19.58,33.92
BEGIN DESCRIPTION:
Surveyed cross-section/XS2
END DESCRIPTION:
XS GIS Cut Line= 4
       3086531.4      13803176.3     3086966.812    13802824.931
      3087049.32    13802795.517     3087299.948     13802550.62
#Sta/Elev= 30
       0   61.36   91.36   60.92  245.56   60.99  373.27   60.31  383.94   59.96
  437.27    60.1  457.59   59.37  511.94   54.83  534.69   55.12  553.96   56.08
   559.5   55.66  573.74   55.61   591.4   49.17   607.3   48.92  626.14   55.77
   647.1   56.69  658.55   56.16  669.16   55.16  679.77   54.97  690.37   55.34
  722.19   57.58  751.57   57.95  777.38   57.74  828.27   55.44  860.09   56.33
   870.7   55.89  902.52   55.84  923.28   55.04  966.16   54.11  997.51   54.01
#Mann= 3 , 0 , 0
       0      .1       0  573.74     .04       0  626.14     .15       0
#XS Ineff= 2 , 0
       0     437             706       0
Permanent Ineff=
       T       T
#Block Obstruct= 1 ,-1
  860.41 1006.69   56.34
Bank Sta=573.74,626.14
XS Rating Curve= 0
Exp/Cntr=.5,.3

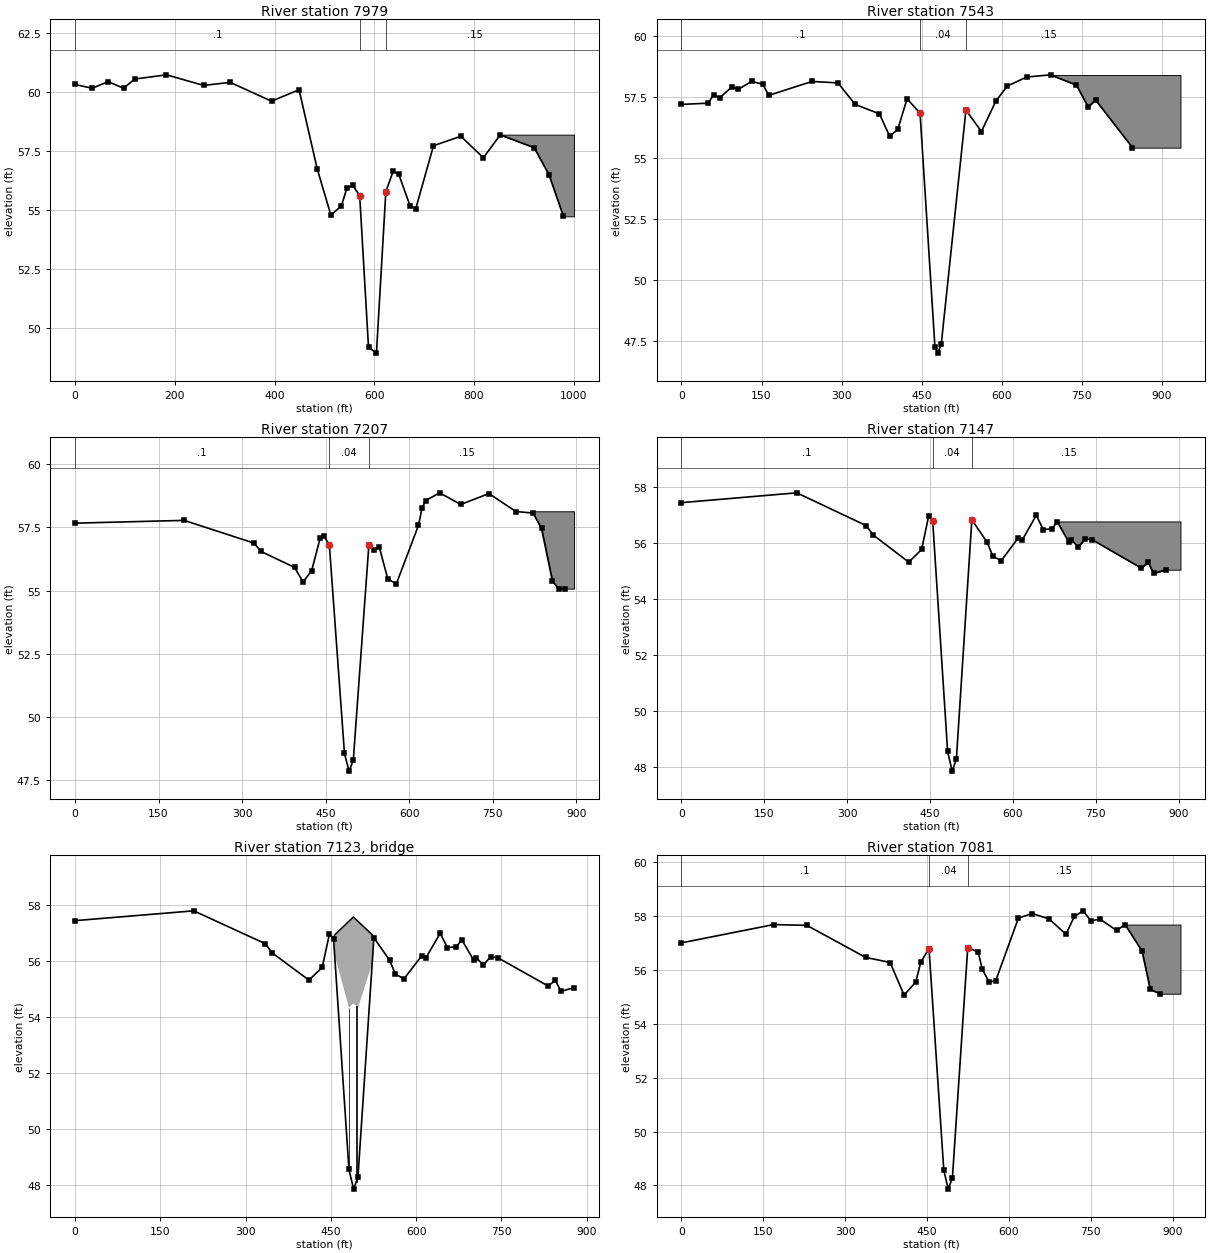
Type RM Length L Ch R = 1 ,7979    ,413.57,435.85,442.88
BEGIN DESCRIPTION:
Copied cross-section 7998/XS1
END DESCRIPTION:
XS GIS Cut Line= 4
      3086557.68     13803206.45     3086976.538     13802841.34
     3087059.047    13802811.926     3087363.806     13802670.81
#Sta/Elev= 30
       0   60.33   34.57   60.17   66.46   60.45   97.32   60.17  119.62   60.56
  183.41   60.74  257.83   60.29  310.99   60.42  394.09   59.62   449.2   60.11
   485.4   56.76  512.98   54.78  534.25   55.18  544.88   55.92  556.67   56.05
  570.74   55.61   588.4   49.17   604.3   48.92  623.14   55.77  637.67   56.64
  649.18   56.51  671.78   55.17  683.08   55.05  718.68   57.73  773.46   58.13
  818.66   57.22  852.55   58.19  920.34   57.65   950.1    56.5  979.09   54.73
#Mann= 3 , 0 , 0
       0      .1       0  570.74     .04       0  623.14     .15       0
#XS Ineff= 2 , 0
       0     434             703       0
Permanent Ineff=
       T       T
#Block Obstruct= 1 ,-1
  852.55 1000.36    58.2
Bank Sta=570.74,623.14
XS Rating Curve= 0
Exp/Cntr=.3,.1

Type RM Length L Ch R = 1 ,7543    ,332.61,336.2,347.61
BEGIN DESCRIPTION:
Surveyed cross-section
END DESCRIPTION:
XS GIS Cut Line= 4
      3086780.76    13803369.086     3087179.278    13803207.386
     3087280.663    13803188.861     3087569.856    13803071.504
#Sta/Elev= 30
       0    57.2   50.44   57.25   60.13    57.6   71.65   57.47   94.68   57.92
  106.19   57.81  131.38   58.14  152.25   58.03  163.76   57.57  244.69   58.14
  293.26   58.08  325.63    57.2  371.04   56.81  390.38   55.89  405.59   56.19
  422.76   57.43  447.13   56.84  474.98   47.29  480.64   47.02  486.94    47.4
  533.14   56.97   562.1   56.09  589.33   57.34  610.66   57.95  646.91   58.32
   691.6   58.41  740.17   57.99  762.06    57.1   776.1   57.38  845.24   55.43
#Mann= 3 , 0 , 0
       0      .1       0  447.13     .04       0  533.14     .15       0
#XS Ineff= 2 , 0
       0     333             590       0
Permanent Ineff=
       T       T
#Block Obstruct= 1 ,-1
  692.39  935.15    58.4
Bank Sta=447.13,533.14
XS Rating Curve= 0
Exp/Cntr=.3,.1

Type RM Length L Ch R = 1 ,7207    ,60.97,60.01,60.5
BEGIN DESCRIPTION:
Copied cross-section 7081/XS4
END DESCRIPTION:
XS GIS Cut Line= 4
      3086847.97     13803622.22     3087281.282     13803524.64
     3087384.799     13803510.37     3087708.798    13803441.959
#Sta/Elev= 30
       0   57.67  195.98   57.78  321.48   56.88  334.03   56.55  394.16   55.92
  409.54   55.34  424.91   55.79  440.29   57.09  447.14   57.17  456.74   56.79
  483.81   48.56  492.01   47.86  499.65   48.29  527.67   56.82  536.57   56.61
  546.34   56.72  561.64   55.46  576.97   55.27  616.65   57.58  622.96   58.25
  629.31   58.56  654.62   58.87   692.6   58.41  743.23   58.84   791.6   58.13
  822.26   58.07  837.59   57.46  857.15   55.38  868.25   55.07   879.8   55.08
#Mann= 3 , 0 , 0
       0      .1       0  456.74     .04       0  527.67     .15       0
#XS Ineff= 2 , 0
       0     356             598       0
Permanent Ineff=
       T       T
#Block Obstruct= 1 ,-1
  818.93  895.91   58.14
Bank Sta=456.74,527.67
XS Rating Curve= 0
Exp/Cntr=.5,.3

Type RM Length L Ch R = 1 ,7147    ,57.79,65.65,71.74
BEGIN DESCRIPTION:
Copied cross-section 7081/XS3
END DESCRIPTION:
XS GIS Cut Line= 4
      3086861.15     13803680.76     3087292.334     13803583.66
      3087394.75     13803569.59      3087719.85    13803500.979
#Sta/Elev= 30
       0   57.43  208.83   57.78  334.52   56.61  346.88   56.28   411.4   55.31
  434.72   55.76   447.6   56.96  454.74   56.79  481.81   48.56  490.01   47.86
  497.65   48.29  525.67   56.82  553.66   56.01   563.5   55.52  578.83   55.36
  609.49   56.17  616.96    56.1  642.28   56.98  654.93   56.47  670.81    56.5
  680.25   56.75  701.47   56.01  705.57   56.11  718.23   55.85  730.89   56.14
  743.55   56.11  832.16    55.1  844.82    55.3  854.78   54.91  877.62   55.04
#Mann= 3 , 0 , 0
       0      .1       0  454.74     .04       0  525.67     .15       0
#XS Ineff= 2 , 0
       0     357             591       0
Permanent Ineff=
       T       T
#Block Obstruct= 1 ,-1
  681.46   903.3   56.76
Bank Sta=454.74,525.67
XS Rating Curve= 0
Exp/Cntr=.5,.3

Type RM Length L Ch R = 3 ,7123    ,,,
BEGIN DESCRIPTION:
Benning Bridge
Roadway profile from LIDAR, bridge elevations from Pate.
0 skew
38' width from HEC2 & DOQQ
66' length from Pate
2 sets of wood circular piers (Pate) 12" dia; spacing of piers from picture (equal spacing??).
END DESCRIPTION:
Bridge Culvert--1,0,-1,-1, 0
Deck Dist Width WeirC Skew NumUp NumDn MinLoCord MaxHiCord MaxSubmerge Is_Ogee
13.825,38,2.6,0, 5, 5, , , .95, 0, 0,0,,
  454.74  456.63  489.63  522.63  525.67
   56.81   56.92   57.56   56.93    56.8
           53.84   54.48   53.85
  453.74  455.63  488.63  521.63  524.67
   56.81   56.92   57.56   56.93   56.83
           53.84   54.48   53.85
Pier Skew, UpSta & Num, DnSta & Num=  ,481.63, 2 ,480.63, 2 , 0 , 0 , 0 ,,
    1.09    1.09
       0     100
    1.09    1.09
       0     100
Pier Skew, UpSta & Num, DnSta & Num=  ,494.63, 2 ,493.63, 2 , 0 , 0 , 0 ,,
    1.09    1.09
       0     100
    1.09    1.09
       0     100
BR Coef=-1 , 1 , 1 ,1.05, 0 ,,,.8,-1,1.2,0,
WSPro=,,,, 1 ,,,, 0 ,,,, 0 ,,,,-1 ,-1 ,-1 , 0 , 0 , 0 , 0 , 0
BC Design=,, 0 ,, 0 ,,,,,,

Type RM Length L Ch R = 1 ,7081    ,42.58,42.46,48.22
BEGIN DESCRIPTION:
Surveyed cross-section/XS2
END DESCRIPTION:
XS GIS Cut Line= 4
       3086871.7     13803727.59     3087301.831    13803640.401
     3087406.683    13803640.947     3087729.347     13803557.72
#Sta/Elev= 30
       0   57.01  169.17   57.69  229.81   57.66  337.53   56.47  382.52   56.28
  407.97   55.07  429.36   55.55  438.88   56.31  453.74   56.79  480.81   48.56
  489.01   47.86  496.65   48.29  524.67   56.82  543.73   56.68  551.34   56.03
  563.65   55.56  575.97    55.6  617.59   57.93  642.69    58.1  673.67    57.9
  704.65   57.33  720.14   57.99  736.06    58.2  751.12   57.82  766.61    57.9
  797.59   57.47  813.09   57.69  844.07   56.71   859.2   55.28  876.96   55.12
#Mann= 3 , 0 , 0
       0      .1       0  453.74     .04       0  524.67     .15       0
#XS Ineff= 2 , 0
       0     357             587       0
Permanent Ineff=
       T       T
#Block Obstruct= 1 ,-1
  813.22  914.59   57.69
Bank Sta=453.74,524.67
XS Rating Curve= 0
Exp/Cntr=.5,.3

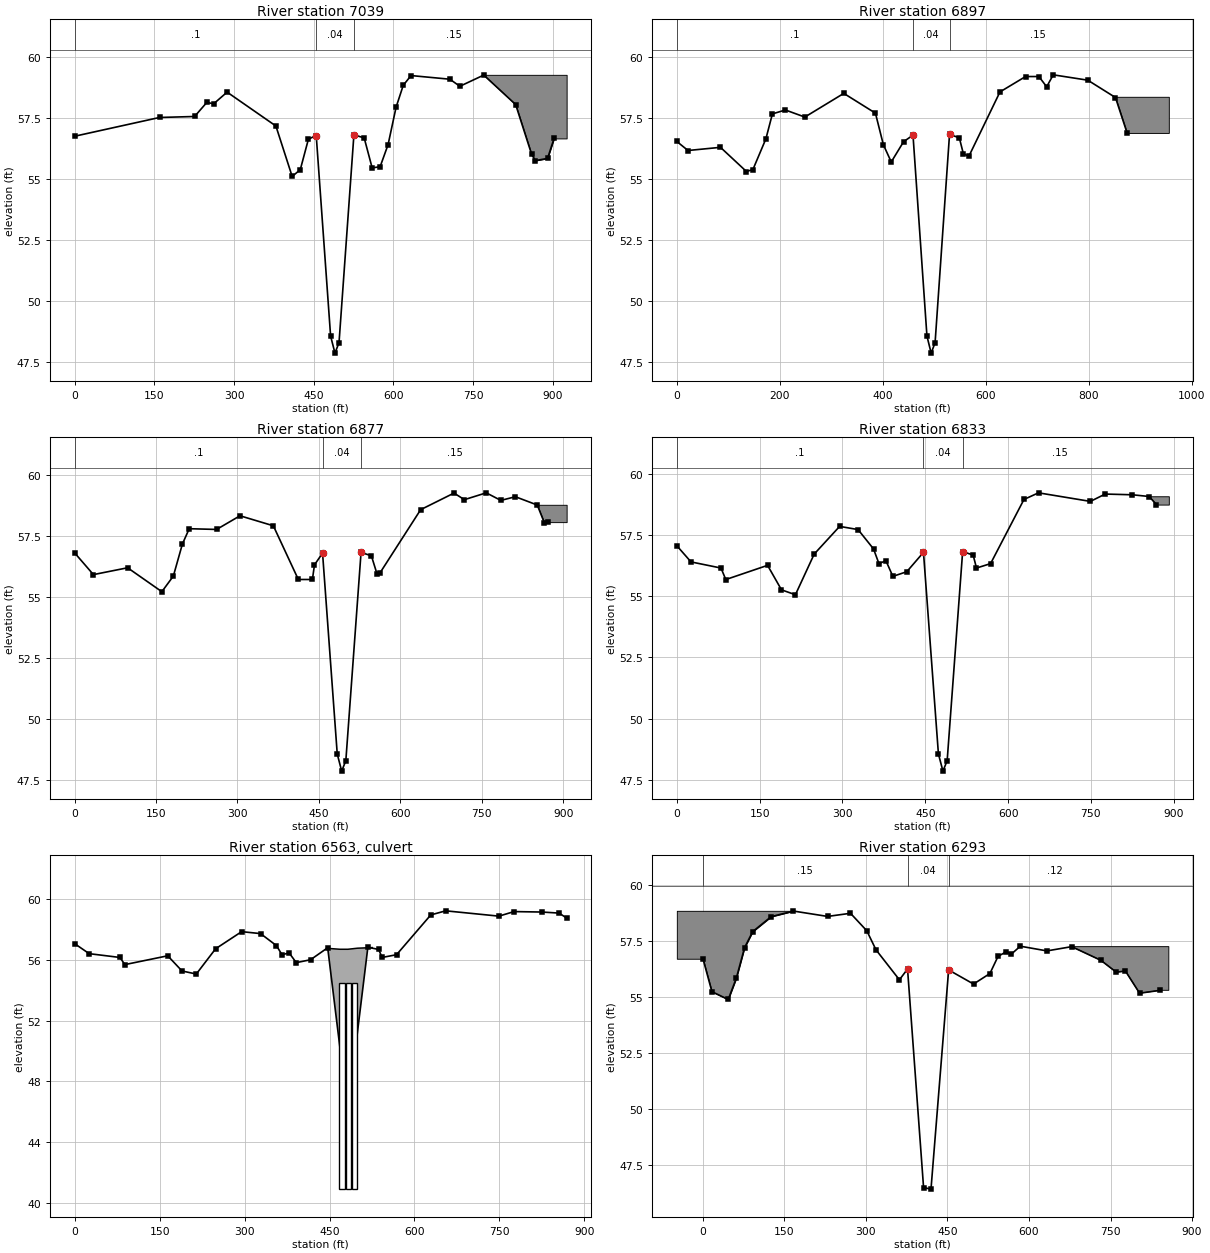
Type RM Length L Ch R = 1 ,7039    ,141.65,141.16,138.16
BEGIN DESCRIPTION:
Copied cross-section 7081/XS1
END DESCRIPTION:
XS GIS Cut Line= 4
     3086876.216    13803769.589     3087306.347      13803682.4
       3087411.2    13803682.946      3087769.77     13803673.59
#Sta/Elev= 30
       0   56.76  159.81   57.53  225.78   57.57  248.89   58.15  261.61   58.09
     287   58.57  378.83   57.18  409.45   55.11  424.75   55.39  440.03   56.64
  454.74   56.79  481.81   48.56  490.01   47.86  497.65   48.29  525.67   56.82
  545.03   56.69  560.04   55.46  575.04   55.51  590.05   56.42  605.05   57.95
  618.55   58.85  633.18   59.25  706.29    59.1  725.09   58.81  770.11   59.27
  830.13   58.06  860.14   56.02  867.15   55.76  890.15   55.85  902.43   56.67
#Mann= 3 , 0 , 0
       0      .1       0  454.74     .04       0  525.67     .15       0
#XS Ineff= 2 , 0
       0     362             593       0
Permanent Ineff=
       T       T
#Block Obstruct= 1 ,-1
     770  926.08   59.28
Bank Sta=454.74,525.67
XS Rating Curve= 0
Exp/Cntr=.3,.1

Type RM Length L Ch R = 1 ,6897    ,20.3,19.99,20.13
BEGIN DESCRIPTION:
Copied cross-section 7081
END DESCRIPTION:
XS GIS Cut Line= 4
      3086885.55      13803916.4     3087315.894     13803822.76
     3087420.747    13803823.306     3087747.443     13803782.31
#Sta/Elev= 30
       0   56.53   21.73   56.16   84.77   56.29   135.2    55.3   147.8   55.38
  173.02   56.64  185.63   57.66  210.84   57.82  248.66   57.53  324.31    58.5
  385.77   57.69  401.12    56.4  416.47   55.69  440.41   56.52  458.74   56.79
  485.81   48.56  494.01   47.86  501.65   48.29  529.67   56.82  548.73   56.68
  556.51   56.03  567.19   55.92  627.66   58.56   677.4   59.19  703.25   59.19
  718.37   58.77  731.13   59.26  798.29   59.04  852.02   58.33  874.53   56.88
#Mann= 3 , 0 , 0
       0      .1       0  458.74     .04       0  529.67     .15       0
#XS Ineff= 2 , 0
       0     361             604       0
Permanent Ineff=
       T       T
#Block Obstruct= 1 ,-1
  850.97  955.63   58.36
Bank Sta=458.74,529.67
XS Rating Curve= 0
Exp/Cntr=.3,.1

Type RM Length L Ch R = 1 ,6877    ,45.66,44.97,45.54
BEGIN DESCRIPTION:
Copied cross-section 7081/XS4
END DESCRIPTION:
XS GIS Cut Line= 4
       3086889.8     13803935.94     3087318.045     13803842.76
     3087422.898    13803843.306     3087749.908     13803802.16
#Sta/Elev= 30
       0    56.8   34.58   55.91   97.62   56.19  160.66   55.21  181.86   55.85
  198.48   57.16  211.09   57.79  261.52   57.76  304.67   58.32  366.07   57.91
  412.12   55.71  438.03   55.71  441.88   56.31  456.74   56.79  483.81   48.56
  492.01   47.86  499.65   48.29  527.67   56.82  546.73   56.68  556.91   55.95
  562.88   55.99  637.48   58.57  698.94   59.25  718.06   58.98  758.34   59.26
   785.2   58.95  812.06    59.1  852.34   58.76  865.24   58.04  872.71   58.06
#Mann= 3 , 0 , 0
       0      .1       0  456.74     .04       0  527.67     .15       0
#XS Ineff= 2 , 0
       0     356             601       0
Permanent Ineff=
       T       T
#Block Obstruct= 1 ,-1
  852.41  906.42   58.77
Bank Sta=456.74,527.67
XS Rating Curve= 0
Exp/Cntr=.5,.3

Type RM Length L Ch R = 1 ,6833    ,524.08,539.81,551.28
BEGIN DESCRIPTION:
Copied cross-section 7081/XS3
END DESCRIPTION:
XS GIS Cut Line= 4
      3086899.37     13803979.91     3087322.884     13803887.76
     3087427.737    13803888.306     3087755.453     13803846.81
#Sta/Elev= 30
       0   57.06   25.67    56.4   79.96   56.15   88.71   55.68  164.35   56.26
  189.57   55.26  214.79   55.06  248.82   56.72  294.87   57.85  328.25   57.72
  356.28   56.93  366.08   56.33  378.69   56.45  391.29   55.81  416.51      56
  446.74   56.79  473.81   48.56  482.01   47.86  489.65   48.29  517.67   56.82
  536.73   56.68  542.74   56.15  568.28   56.33  628.76   58.95   655.1   59.22
  749.04   58.87  775.88   59.17  825.31   59.14  855.55   59.07  868.61   58.74
#Mann= 3 , 0 , 0
       0      .1       0  446.74     .04       0  517.67     .15       0
#XS Ineff= 2 , 0
       0     351             596       0
Permanent Ineff=
       T       T
#Block Obstruct= 1 ,-1
  855.28  891.12   59.08
Bank Sta=446.74,517.67
XS Rating Curve= 0
Exp/Cntr=.5,.3

Type RM Length L Ch R = 2 ,6563    ,,,
BEGIN DESCRIPTION:
Bellfort Culvert
Roadway profile from Pate only; LIDAR doesn't align with Pate survey.
0 skew (for culverts)
144' long culvert (2.5 m DOQQ)
3 cells
10' x 13.6' (Pate) .
END DESCRIPTION:
Bridge Culvert--1,0,-1,-1, 0
Deck Dist Width WeirC Skew NumUp NumDn MinLoCord MaxHiCord MaxSubmerge Is_Ogee
4.905,530,2.6,0, 5, 5, , , .95, 0, 0,0,,
  446.74  468.36  482.36  499.36  525.28
   56.75   56.69   56.69   56.76    56.8
                                        
  376.51  400.24  414.24  431.24  452.14
   56.24   56.69   56.69   56.76   56.18
                                        
BR Coef=-1 , 0 , 0 ,, 0 ,,,.8,-1,,0,
WSPro=,,,, 1 ,,,, 0 ,,,, 0 ,,,,-1 ,-1 ,-1 , 0 , 0 , 0 , 0 , 0
Multiple Barrel Culv=2,13.6,10,530,.014,.5,1,8,2,40.9,40.2, 3,Culvert #1  , 0 ,4.905
  472.36  404.24  483.36  415.24  494.36  426.24
Culvert Bottom n=.014
BC Design=,, 0 ,, 0 ,,,,,,

Type RM Length L Ch R = 1 ,6293    ,45.08,45.42,45.23
BEGIN DESCRIPTION:
Surveyed cross-section 6196/XS2
END DESCRIPTION:
XS GIS Cut Line= 5
     3086931.015    13804422.877     3087310.609     13804418.73
     3087391.394    13804433.651     3087628.637    13804452.327
     3087754.408    13804518.307
#Sta/Elev= 30
       0   56.72   16.49   55.25   46.49    54.9   61.49   55.86   76.49   57.21
   91.49   57.93   125.5    58.6  166.49   58.85  229.37   58.61   271.5   58.75
   301.5   57.97   318.4   57.12  361.51   55.78  376.51   56.26  405.99    46.5
  419.65   46.43  452.11   56.22  497.99   55.59  528.08   56.06  543.12   56.83
  558.17   57.03  567.66   56.93  583.99   57.28  632.99   57.07  678.54   57.26
  732.27   56.65  760.57   56.12  777.51   56.17  803.53   55.18  841.77   55.31
#Mann= 3 , 0 , 0
       0     .15       0  376.51     .04       0  452.11     .12       0
#XS Ineff= 2 , 0
       0     333             506       0
Permanent Ineff=
       T       T
#Block Obstruct= 2 ,-1
  -48.07  166.57   58.86  678.25  857.31   57.26
Bank Sta=376.51,452.11
XS Rating Curve= 0
Exp/Cntr=.5,.3