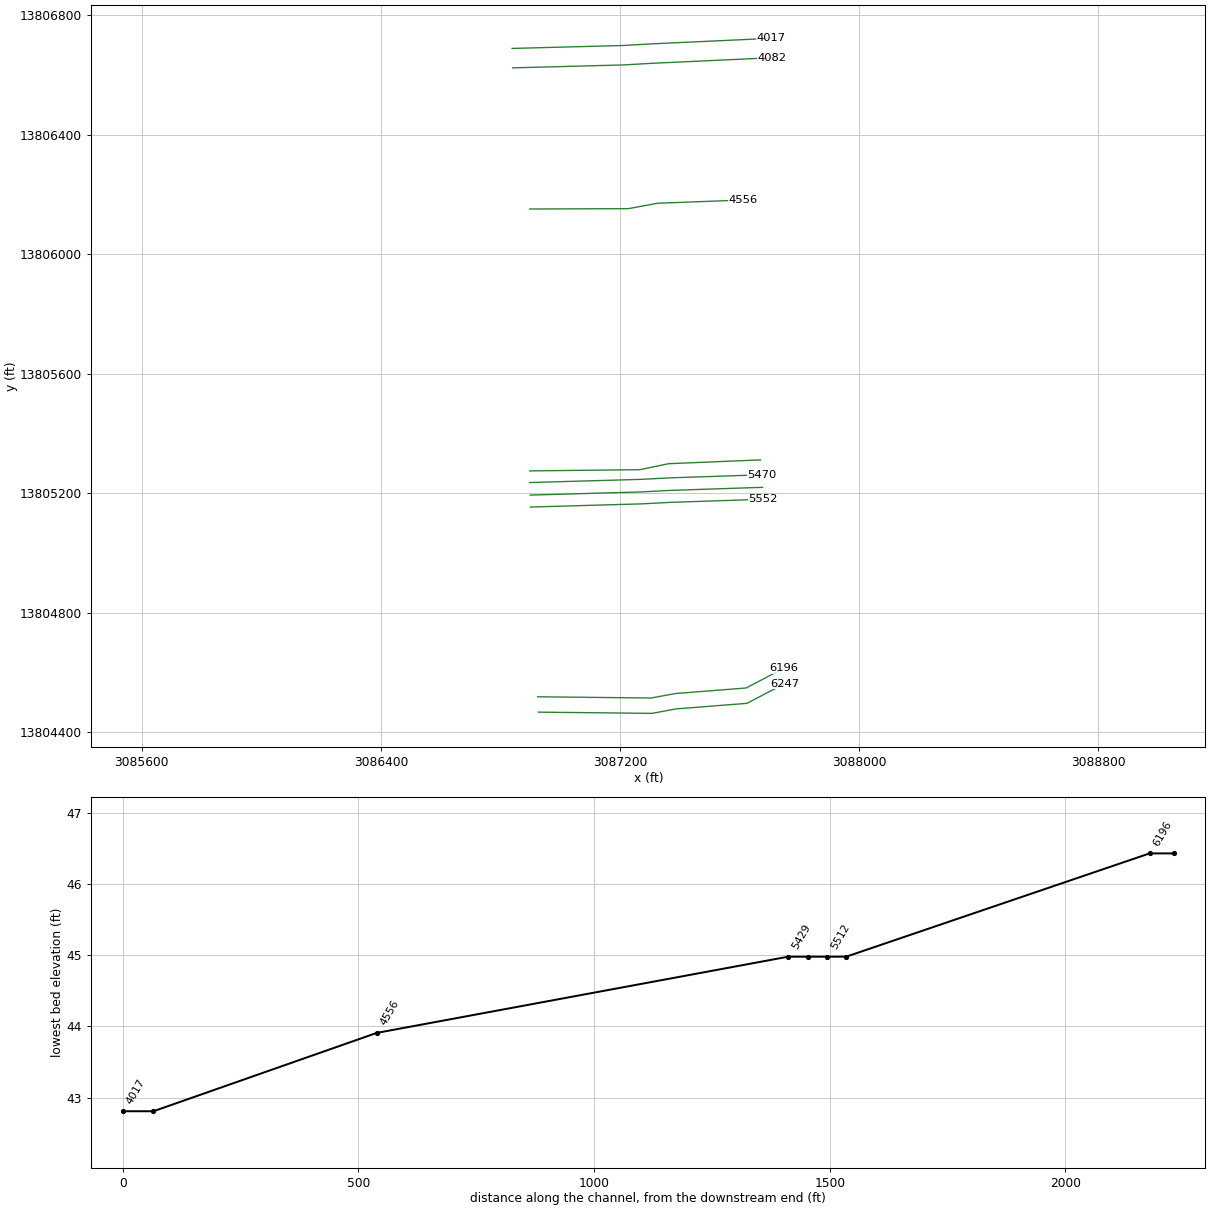
HEC-RAS study D139-00-00.prj: D139-00-00

--- D139-00-00.g01 (geometry) --- (continued)

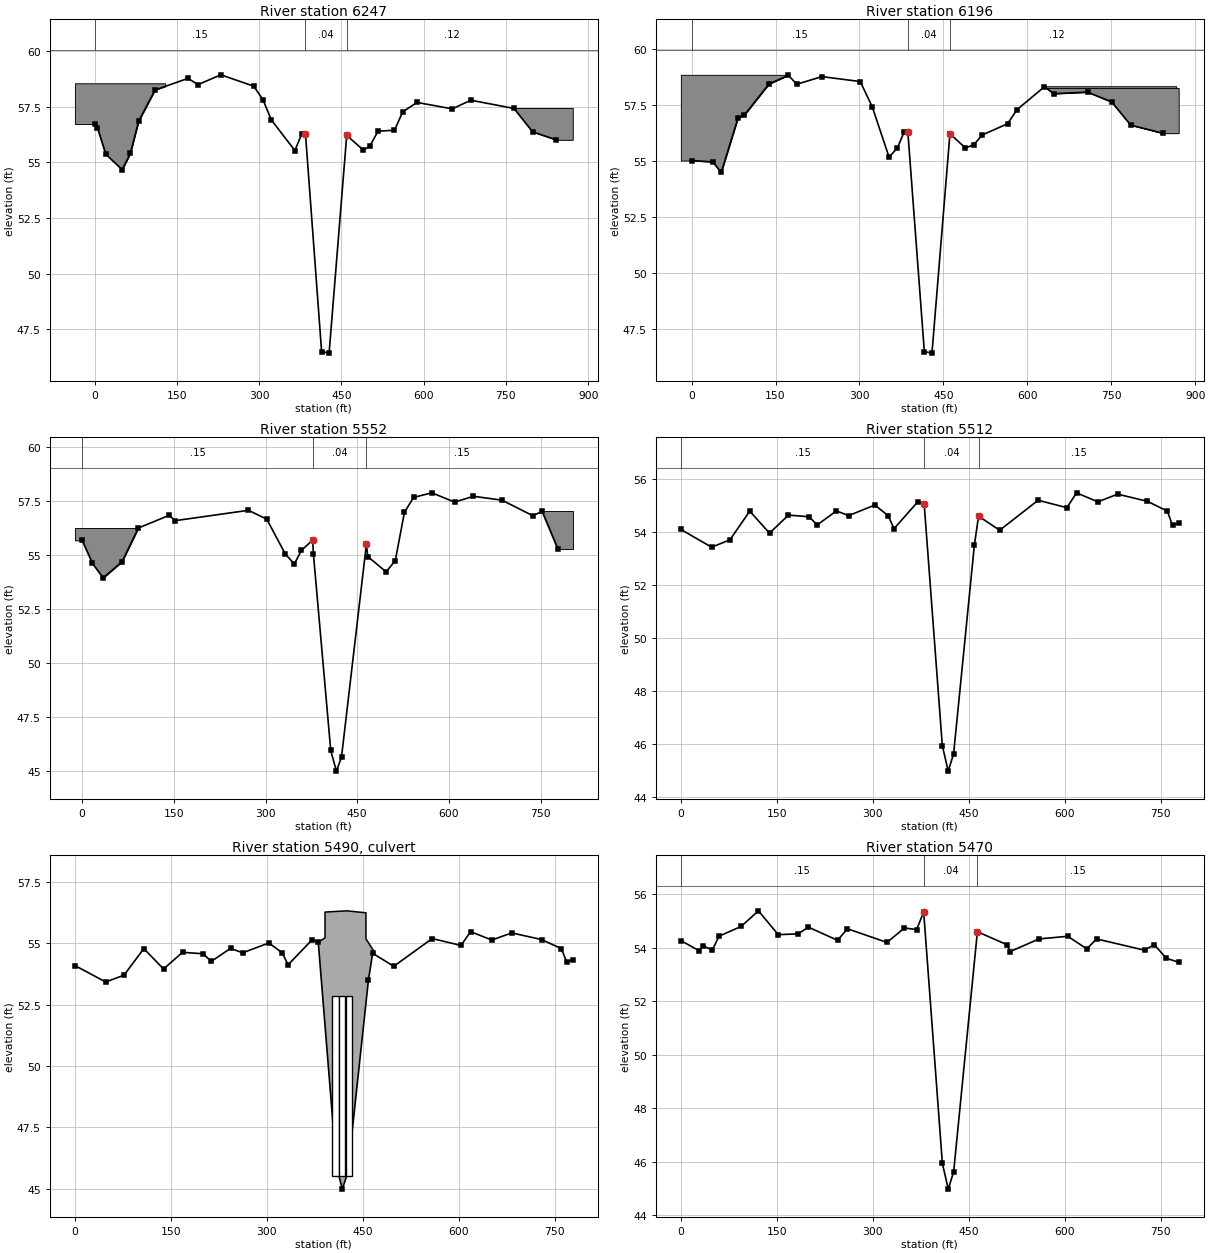
Type RM Length L Ch R = 1 ,6247    ,51.43,51.52,51.47
BEGIN DESCRIPTION:
Surveyed cross-section 6196/XS1
END DESCRIPTION:
XS GIS Cut Line= 5
      3086927.26    13804467.917     3087306.854     13804463.77
     3087387.639    13804478.691     3087624.882    13804497.367
     3087750.653    13804563.347
#Sta/Elev= 30
       0   56.72    5.24   56.55   20.24   55.37   50.24   54.67   65.24    55.4
   80.24   56.84  110.25   58.25  170.25   58.77  188.61   58.49  230.25   58.93
  290.26   58.42  307.32    57.8  322.16   56.91  365.26   55.53  377.62   56.27
  384.52   56.29  413.99    46.5  427.65   46.43  459.77   56.21  490.13   55.55
  501.75   55.72   516.8    56.4  546.89   56.44  561.94   57.27  588.13   57.69
  652.22    57.4  686.12   57.79  764.81   57.42  798.69   56.37  841.77   56.01
#Mann= 3 , 0 , 0
       0     .15       0  384.52     .04       0  459.77     .12       0
#XS Ineff= 2 , 0
       0     331             508       0
Permanent Ineff=
       T       T
#Block Obstruct= 3 ,-1
  -35.83  128.73   58.55  463.03  548.35   49.89  764.67  871.95   57.44
Bank Sta=384.52,459.77
XS Rating Curve= 0
Exp/Cntr=.3,.1

Type RM Length L Ch R = 1 ,6196    ,649.09,643.69,638.07
BEGIN DESCRIPTION:
Surveyed cross-section
END DESCRIPTION:
XS GIS Cut Line= 5
      3086924.53     13804519.29     3087304.124    13804515.143
      3087384.91    13804530.064     3087622.152     13804548.74
     3087747.923     13804614.72
#Sta/Elev= 30
       0   55.01   37.97   54.95   52.97   54.48   82.97   56.91   93.74   57.02
  138.26   58.42  172.98   58.81  187.98   58.41  232.98   58.75  301.48   58.53
  322.99    57.4  352.99   55.16  367.99   55.58  379.62   56.27  386.52   56.29
  415.99    46.5  429.65   46.43  461.77   56.21  462.45   56.19  489.44   55.57
  504.49   55.72  519.54   56.15  564.68   56.65   581.7   57.28   630.7    58.3
  647.03   57.99  707.84   58.06  750.95   57.62  784.83   56.59  841.77   56.23
#Mann= 3 , 0 , 0
       0     .15       0  386.52     .04       0  462.45     .12       0
#XS Ineff= 2 , 0
       0     327             511       0
Permanent Ineff=
       T       T
#Block Obstruct= 3 ,-1
  -19.14  172.66   58.83  630.17  867.03    58.3  631.06  870.59   58.24
Bank Sta=386.52,462.45
XS Rating Curve= 0
Exp/Cntr=.3,.1

Type RM Length L Ch R = 1 ,5552    ,40.01,39.98,40
BEGIN DESCRIPTION:
Surveyed cross-section 5429/XS4
END DESCRIPTION:
XS GIS Cut Line= 4
      3086900.56     13805153.99     3087272.091     13805164.61
     3087370.554     13805169.74     3087678.425     13805179.95
#Sta/Elev= 30
       0   55.67   16.95    54.6   34.43   53.93   65.32   54.68   91.98   56.24
  142.56   56.83     152   56.58  272.05   57.06  302.06   56.65  332.08   55.05
  347.08   54.57  358.83   55.21   377.1   55.68  378.34   55.04  406.67   45.94
  415.89   44.98  424.29   45.63  465.02   55.49  467.22   54.92  497.24   54.21
  512.25   54.73  527.26   56.97  542.26   57.66  572.28   57.87  609.14   57.44
  640.19   57.71  686.76   57.53  737.37   56.81  752.38   57.01  778.32   55.26
#Mann= 3 , 0 , 0
       0     .15       0   377.1     .04       0  465.02     .15       0
#XS Ineff= 2 , 0
       0     306             524       0
Permanent Ineff=
       T       T
#Block Obstruct= 2 ,-1
  -11.77   91.88   56.24  752.17  802.56   57.01
Bank Sta=377.1,465.02
XS Rating Curve= 0
Exp/Cntr=.5,.3

Type RM Length L Ch R = 1 ,5512    ,42.01,41.98,41.99
BEGIN DESCRIPTION:
Surveyed cross-section 5429/XS3
END DESCRIPTION:
XS GIS Cut Line= 4
      3086899.42     13805193.97     3087271.451     13805204.61
     3087369.852     13805209.74     3087677.099     13805219.93
#Sta/Elev= 30
       0   54.09    48.1   53.42   76.78    53.7  107.67   54.78  138.57   53.95
  168.15   54.63  200.36   54.57  213.17   54.26  243.18   54.79  262.15   54.61
   303.2   55.01  323.94   54.61  333.22   54.12  370.29   55.13  380.34   55.04
  408.67   45.94  417.89   44.98  426.29   45.63  458.74   53.49  465.32   54.59
  498.38   54.06  558.41   55.19  603.44   54.91  618.45   55.47   651.7   55.13
  682.75   55.42  729.32   55.15  760.37   54.78  768.53   54.24  778.13   54.33
#Mann= 3 , 0 , 0
       0     .15       0  380.34     .04       0  465.32     .15       0
#XS Ineff= 2 , 0
       0     304             524       0
Permanent Ineff=
       T       T
Bank Sta=380.34,465.32
XS Rating Curve= 0
Exp/Cntr=.5,.3

Type RM Length L Ch R = 2 ,5490    ,,,
BEGIN DESCRIPTION:
Kinglet Culvert
Roadway profile from SL and Pate survey.
Inverts not yet determined, current data is good estimate.
0 skew
42' long culvert (HEC-2 & 2.5 m DOQQ)
3 cells
10' x 8' (Pate)  conficting information.
END DESCRIPTION:
Bridge Culvert--1,0,-1,-1, 0
Deck Dist Width WeirC Skew NumUp NumDn MinLoCord MaxHiCord MaxSubmerge Is_Ogee
4.98,32,2.6,0, 7, 7, , , .95, 0, 0,0,,
  380.35  390.89  390.89  424.89  454.89  454.89  468.37
   55.04   55.22   56.27   56.32   56.24   55.18   54.63
       0       0       0       0       0       0       0
  379.49  390.89  390.89  424.89  454.89  454.89  463.42
   55.29   55.22   56.27   56.32   56.24   55.18    54.6
       0       0       0       0       0       0       0
BR Coef=-1 , 0 , 0 ,, 0 ,,,.8,-1,,0,
WSPro=,,,, 1 ,,,, 0 ,,,, 0 ,,,,-1 ,-1 ,-1 , 0 , 0 , 0 , 0 , 0
Multiple Barrel Culv=2,7.32,10,32,.014,.5,1,8,2,45.53,45.53, 3,Culvert #1  , 0 ,4.98
  407.01  407.01  417.89  417.89  428.77  428.77
Culvert Bottom n=.014
BC Design=,, 0 ,, 0 ,,,,,,

Type RM Length L Ch R = 1 ,5470    ,32.9,41.05,47.69
BEGIN DESCRIPTION:
Surveyed cross-section 5429/XS2
END DESCRIPTION:
XS GIS Cut Line= 4
      3086898.22     13805235.96     3087270.778     13805246.61
     3087369.114     13805251.73     3087675.706      13805261.9
#Sta/Elev= 30
       0   54.26   28.57   53.88   34.29   54.06    49.3   53.91   59.46   54.42
   94.32   54.79  121.25   55.37  152.15   54.48  183.04   54.51  199.36   54.76
  244.84   54.27  260.28    54.7  322.07   54.19  349.42   54.73  368.42   54.67
  379.44   55.33  408.67   45.94  417.89   44.98  426.29   45.63  463.38   54.59
  510.11    54.1  514.59   53.85  559.61   54.32  604.64   54.42  634.29   53.95
  649.66   54.32   724.7    53.9  739.71   54.11  758.48    53.6  777.94   53.45
#Mann= 3 , 0 , 0
       0     .15       0  379.44     .04       0  463.38     .15       0
#XS Ineff= 2 , 0
       0     304             524       0
Permanent Ineff=
       T       T
Bank Sta=379.44,463.38
XS Rating Curve= 0
Exp/Cntr=.5,.3

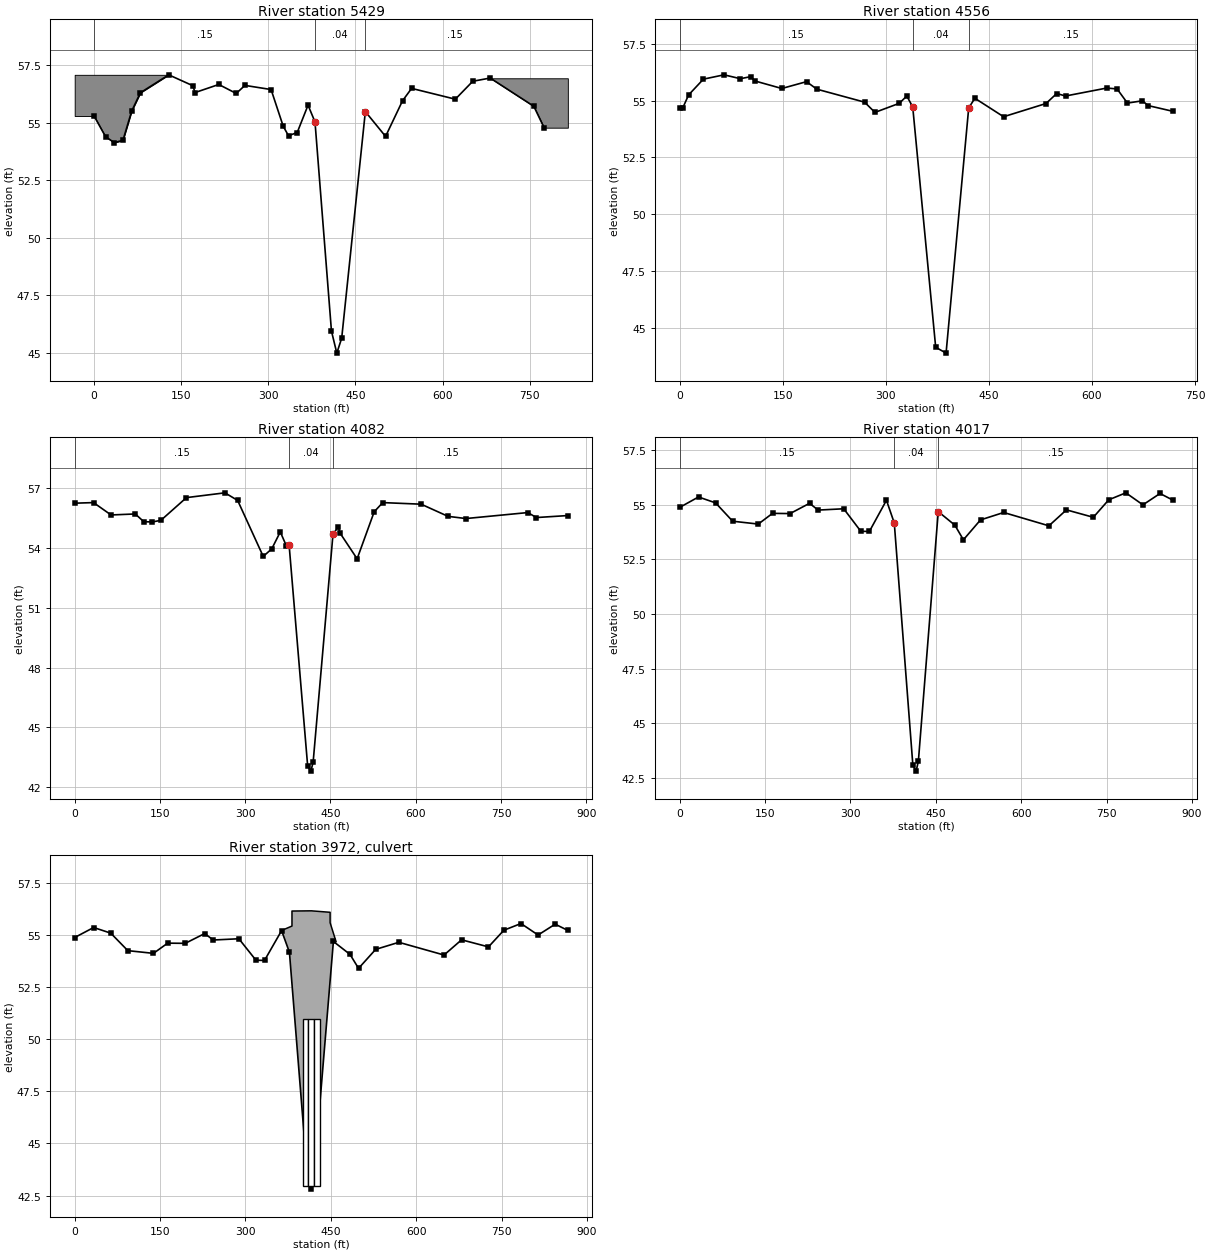
Type RM Length L Ch R = 1 ,5429    ,874.52,872.96,871.93
BEGIN DESCRIPTION:
Surveyed cross-section/XS1
END DESCRIPTION:
XS GIS Cut Line= 4
     3086897.787    13805274.953     3087266.138     13805278.88
     3087362.716    13805298.986     3087670.165    13805311.732
#Sta/Elev= 30
       0    55.3   19.71    54.4   34.71   54.14   49.72   54.24   64.72   55.51
   79.72   56.31  128.54   57.09  169.72   56.62  174.03   56.32  214.73   56.67
  244.73   56.28  259.73   56.63  304.73   56.45  325.66   54.85  334.73   54.44
  349.73   54.58  368.37   55.77  380.34   55.04  408.67   45.94  417.89   44.98
  426.29   45.63  467.02   55.49  501.83   54.41     531   55.96  546.66    56.5
  621.94   56.03  651.96   56.81  681.99   56.95  757.05   55.72  774.73   54.79
#Mann= 3 , 0 , 0
       0     .15       0  380.34     .04       0  467.02     .15       0
#XS Ineff= 2 , 0
       0     304             525       0
Permanent Ineff=
       T       T
#Block Obstruct= 2 ,-1
  -33.35  128.11   57.09  681.83  815.62   56.94
Bank Sta=380.34,467.02
XS Rating Curve= 0
Exp/Cntr=.3,.1

Type RM Length L Ch R = 1 ,4556    ,480.41,473.88,468.8
BEGIN DESCRIPTION:
Surveyed cross-section
END DESCRIPTION:
XS GIS Cut Line= 4
     3086897.787    13806150.982     3087228.368    13806152.201
     3087325.774     13806170.26     3087613.323    13806181.075
#Sta/Elev= 30
       0   54.66    4.71   54.68   13.24   55.25   34.71   55.94   64.71   56.13
   88.52   55.96  103.58   56.05  109.71   55.86  148.74   55.53  184.71   55.83
  199.71    55.5  269.19   54.93  284.24   54.48  319.72   54.88  330.58    55.2
  339.21   54.72   372.6   44.17  387.72   43.91  420.66   54.68  429.65    55.1
   471.4   54.29   533.1   54.87  548.69   55.31  561.47    55.2  621.51   55.55
  636.52   55.51  651.53   54.89  673.47   54.99  681.55   54.78   717.4   54.53
#Mann= 3 , 0 , 0
       0     .15       0  339.21     .04       0  420.66     .15       0
#XS Ineff= 2 , 0
       0     265             500       0
Permanent Ineff=
       T       T
Bank Sta=339.21,420.66
XS Rating Curve= 0
Exp/Cntr=.3,.1

Type RM Length L Ch R = 1 ,4082    ,65.02,65.01,65.01
BEGIN DESCRIPTION:
Surveyed cross-section 3860/XS4
END DESCRIPTION:
XS GIS Cut Line= 4
      3086840.93     13806623.18     3087212.275     13806632.98
     3087303.061    13806638.215     3087707.804       13806657.
#Sta/Elev= 30
       0   56.25   33.14   56.28   63.96   55.66  106.61   55.71  121.61   55.32
  136.62   55.31  151.62   55.39  196.64   56.53  264.31   56.77  286.67   56.39
  331.69   53.58  346.69   53.96   361.7   54.81  372.22   54.12  377.17   54.17
  409.82   43.08  415.54   42.81  419.52   43.27  454.41   54.69  463.67   55.06
  466.85   54.75  496.89   53.46  526.92   55.82  541.94   56.28  609.55    56.2
  656.79   55.59  688.28   55.48  797.21   55.78  812.23   55.53  867.59   55.63
#Mann= 3 , 0 , 0
       0     .15       0  377.17     .04       0  454.41     .15       0
#XS Ineff= 2 , 0
       0     301             543       0
Permanent Ineff=
       T       T
Bank Sta=377.17,454.41
XS Rating Curve= 0
Exp/Cntr=.5,.3

Type RM Length L Ch R = 1 ,4017    ,90.01,89.99,90
BEGIN DESCRIPTION:
Surveyed cross-section 3860/XS3
END DESCRIPTION:
XS GIS Cut Line= 4
      3086839.22     13806688.16     3087209.735     13806697.94
     3087300.521    13806703.175     3087704.716     13806721.93
#Sta/Elev= 30
       0   54.88   33.29   55.36    63.3   55.09   93.31   54.25  138.33   54.12
  163.31   54.61  194.13    54.6  228.36   55.07  243.36   54.76  288.38   54.82
  318.39   53.79   333.4   53.78  363.41   55.21  377.17   54.17  409.82   43.08
  415.54   42.81  419.52   43.27  454.41   54.69  483.58   54.07   498.6    53.4
  528.63   54.31  569.35   54.65  648.76   54.04  679.57   54.77  726.81   54.43
  753.87   55.23  783.91   55.55  813.94      55  843.97   55.52  866.21   55.22
#Mann= 3 , 0 , 0
       0     .15       0  377.17     .04       0  454.41     .15       0
#XS Ineff= 2 , 0
       0     294             547       0
Permanent Ineff=
       T       T
Bank Sta=377.17,454.41
XS Rating Curve= 0
Exp/Cntr=.5,.3

Type RM Length L Ch R = 2 ,3972    ,,,
BEGIN DESCRIPTION:
Willowbend Culvert.  TOC data for right end of the rail is revised according to additional field measurment.
END DESCRIPTION:
Bridge Culvert--1,0,-1,-1, 0
Deck Dist Width WeirC Skew NumUp NumDn MinLoCord MaxHiCord MaxSubmerge Is_Ogee
4.995,80,2.6,0, 7, 7, , , .95, 0, 0,0,,
  363.67  381.64  381.64  415.64  448.64  448.64  459.11
   55.22   55.43   56.15   56.16   56.09   55.59   54.68
       0       0       0       0       0       0       0
  365.75  378.64  378.64  412.64  445.64  445.64  460.64
   54.73   55.43   56.15   56.16   56.09   55.59   55.05
       0       0       0       0       0       0       0
Multiple Barrel Culv=2,8,10,80,.014,.5,1,8,2,42.95,42.9, 3,Culvert #1  , 0 ,4.995
  405.34  402.34  415.54  412.54  425.74  422.74
Culvert Bottom n=.014
BC Design=,, 0 ,, 0 ,,,,,,