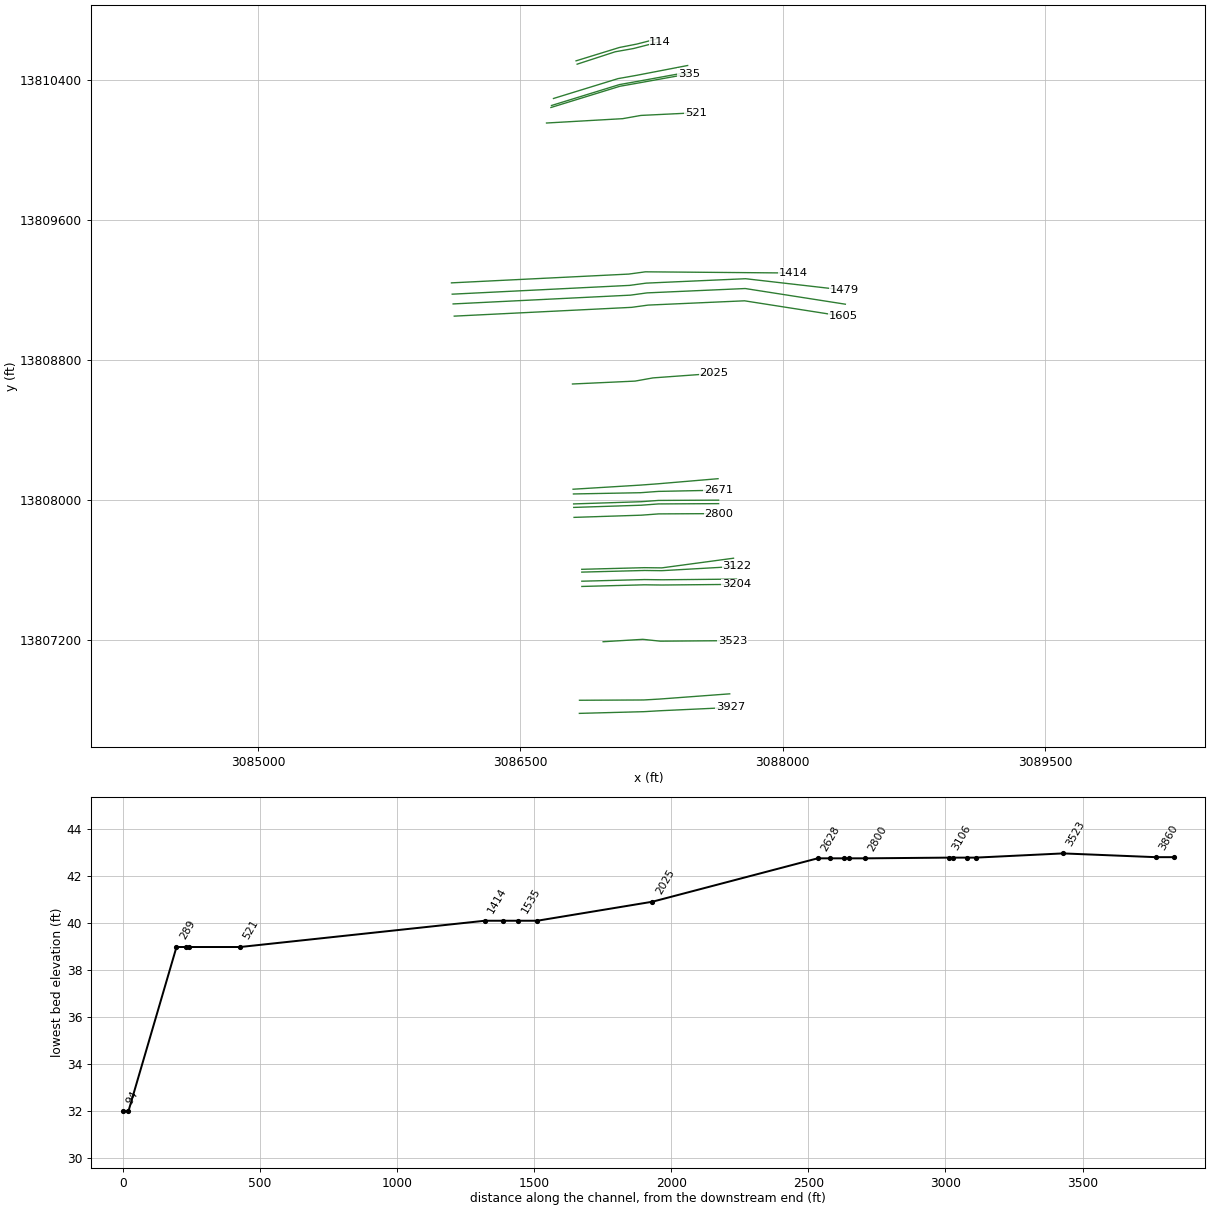
HEC-RAS study D139-00-00.prj: D139-00-00

--- D139-00-00.g01 (geometry) --- (continued)

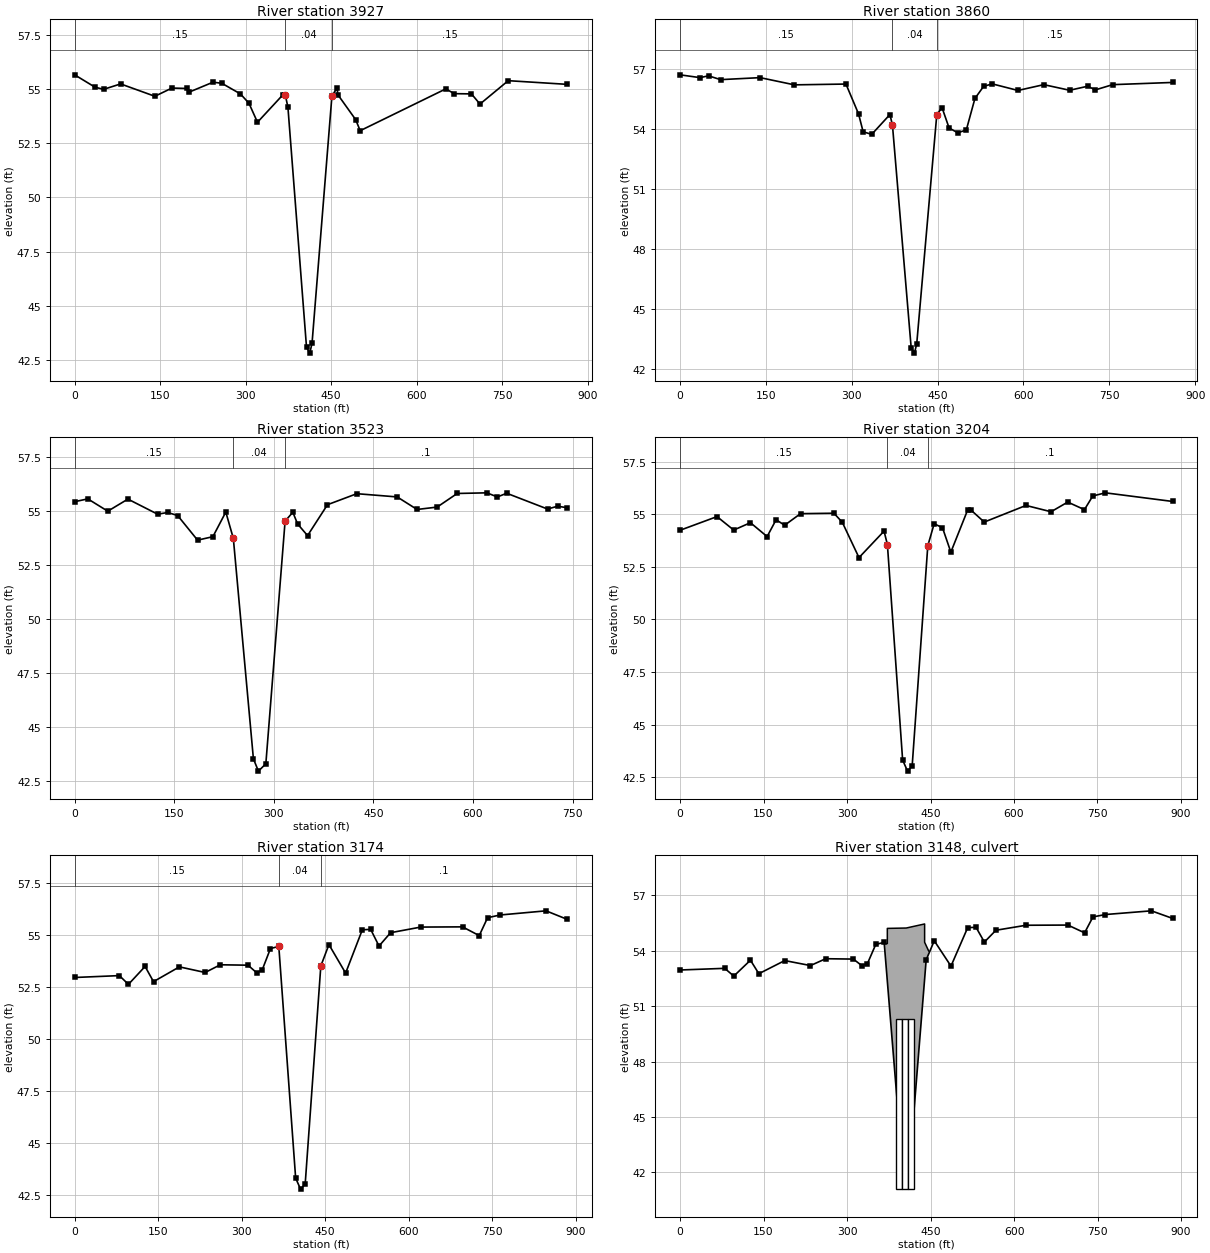
Type RM Length L Ch R = 1 ,3927    ,67.87,66.89,67.89
BEGIN DESCRIPTION:
Surveyed cross-section 3860/XS2
END DESCRIPTION:
XS GIS Cut Line= 4
      3086836.85     13806778.13     3087206.217     13806787.87
     3087297.003    13806793.105      3087700.44     13806811.83
#Sta/Elev= 30
       0   55.66   35.66   55.09   50.67   54.99   80.68   55.24   140.7   54.67
  170.71   55.05  196.53   55.03  200.72   54.86  242.76   55.32  258.18   55.27
  290.75   54.78  305.76   54.35  320.76   53.47  365.78   54.75  369.73   54.71
  374.17   54.17  406.82   43.08  412.54   42.81  416.52   43.27  451.41   54.69
  460.67   55.06  461.59   54.75  493.08   53.59  500.97   53.08  651.13   55.01
  666.15   54.79  696.18   54.78   711.2   54.31  760.78   55.39   864.3   55.22
#Mann= 3 , 0 , 0
       0     .15       0  369.73     .04       0  451.41     .15       0
#XS Ineff= 2 , 0
       0     292             580       0
Permanent Ineff=
       T       T
Bank Sta=369.73,451.41
XS Rating Curve= 0
Exp/Cntr=.5,.3

Type RM Length L Ch R = 1 ,3860    ,346.56,337.6,329.53
BEGIN DESCRIPTION:
Surveyed cross-section/XS1
END DESCRIPTION:
XS GIS Cut Line= 4
     3086837.602    13806853.144      3087204.33    13806854.759
     3087295.116    13806859.995     3087696.914    13806889.923
#Sta/Elev= 30
       0   56.69    34.9   56.55    49.9   56.64   70.85   56.45   139.9   56.55
   199.9   56.19   289.9   56.23  311.92   54.74   319.9   53.85   334.9   53.72
  366.73   54.71  371.17   54.17  403.82   43.08  409.54   42.81  413.52   43.27
  448.58    54.7  457.67   55.06  470.09   54.04  485.13    53.8  500.17   53.94
  515.21   55.51  530.25   56.11  545.29   56.24  590.42   55.91  635.54    56.2
  680.67   55.92  712.15   56.12  725.79   55.94  755.88    56.2  860.58   56.31
#Mann= 3 , 0 , 0
       0     .15       0  371.17     .04       0  448.58     .15       0
#XS Ineff= 2 , 0
       0     304             610       0
Permanent Ineff=
       T       T
Bank Sta=371.17,448.58
XS Rating Curve= 0
Exp/Cntr=.3,.1

Type RM Length L Ch R = 1 ,3523    ,312.63,318.69,321.81
BEGIN DESCRIPTION:
Surveyed cross-section
END DESCRIPTION:
XS GIS Cut Line= 4
     3086972.722    13807187.911     3087199.947    13807201.693
     3087300.354    13807190.987     3087713.632    13807194.193
#Sta/Elev= 30
       0   55.44   19.81   55.57   49.87      55   80.19   55.56  125.01   54.86
  140.03   54.94  155.06    54.8  185.12   53.66  208.17   53.82  227.64   54.96
  238.99   53.74  269.21   43.54  276.76   42.97  287.95   43.31  316.94   54.54
  328.62   54.95  335.76   54.41  350.77   53.87  380.77    55.3     425   55.81
  485.77   55.66  515.71   55.08  545.94   55.19  576.18   55.82  620.77   55.85
  636.65   55.66  650.77   55.83  712.24    55.1  727.36   55.23  741.91   55.16
#Mann= 3 , 0 , 0
       0     .15       0  238.99     .04       0  316.94      .1       0
#XS Ineff= 2 , 0
       0     179             670       0
Permanent Ineff=
       T       T
Bank Sta=238.99,316.94
XS Rating Curve= 0
Exp/Cntr=.3,.1

Type RM Length L Ch R = 1 ,3204    ,30,30.04,30.01
BEGIN DESCRIPTION:
Surveyed cross-section 3106/XS4
END DESCRIPTION:
XS GIS Cut Line= 4
     3086851.076     13807504.09     3087209.292     13807513.44
     3087308.774     13807512.29     3087735.888     13807516.06
#Sta/Elev= 30
       0   54.24   66.45   54.89   96.46   54.25  126.47    54.6  156.48   53.94
  172.58   54.74  187.98   54.48   216.5   55.03  276.52   55.05  291.52   54.62
  321.53   52.94  366.55    54.2  372.56   53.56  399.92   43.32  408.72   42.79
  417.05   43.03  445.14    53.5  456.55   54.55  471.55   54.36  486.55    53.2
  516.55   55.19  521.91   55.22  546.56   54.63  621.56   55.42  666.56   55.12
  696.56   55.58  726.56   55.22  741.56   55.87  764.06   56.02  884.96   55.61
#Mann= 3 , 0 , 0
       0     .15       0  372.56     .04       0  445.14      .1       0
#XS Ineff= 2 , 0
       0     314             787       0
Permanent Ineff=
       T       T
Bank Sta=372.56,445.14
XS Rating Curve= 0
Exp/Cntr=.5,.3

Type RM Length L Ch R = 1 ,3174    ,52.02,52.09,54.13
BEGIN DESCRIPTION:
Surveyed cross-section 3106/XS3
END DESCRIPTION:
XS GIS Cut Line= 4
     3086850.951     13807534.09     3087209.167     13807543.44
     3087308.649     13807542.29     3087735.579     13807546.06
#Sta/Elev= 30
       0   52.95   80.26   53.04   96.58   52.62  126.48   53.48   141.6   52.75
  188.11   53.46  234.33   53.19  261.64   53.56  311.37   53.54  326.78   53.18
  336.66    53.3  351.67   54.34  366.67   54.44  396.92   43.32  405.72   42.79
  414.05   43.03  442.14    53.5  456.68   54.53  486.68   53.16  516.68   55.24
  531.68   55.26  546.68   54.46  567.44    55.1  621.68   55.37  696.69   55.38
  726.69   54.96  741.69   55.82  764.18   55.95  846.69   56.15  884.77   55.74
#Mann= 3 , 0 , 0
       0     .15       0  366.67     .04       0  442.14      .1       0
#XS Ineff= 2 , 0
       0     314             784       0
Permanent Ineff=
       T       T
Bank Sta=366.67,442.14
XS Rating Curve= 0
Exp/Cntr=.5,.3

Type RM Length L Ch R = 2 ,3148    ,,,
BEGIN DESCRIPTION:
Cheena Culvert
Roadway profile from SL and Pate bridge info.
Inverts not yet determined, current data is estimate.
0 skew
42' long culvert (hec2 and doqq)
3 cells
10' x 10' (Pate)  Confirm size with Pate
END DESCRIPTION:
Bridge Culvert--1,0,-1,-1, 0
Deck Dist Width WeirC Skew NumUp NumDn MinLoCord MaxHiCord MaxSubmerge Is_Ogee
5.045,42,2.6,0, 7, 7, , , .95, 0, 0,0,,
  366.66  372.35  372.35  406.35  439.35  439.35  446.59
   54.38   54.38    55.2   55.22   55.44   54.45   53.98
       0       0       0       0       0       0       0
  366.88  371.35  371.35  405.35  438.35  438.35  441.89
   53.95   54.38    55.2   55.22   55.44   54.45   54.19
       0       0       0       0       0       0       0
BR Coef=-1 , 0 , 0 ,, 0 ,,,.8,-1,,0,
WSPro=,,,, 1 ,,,, 0 ,,,, 0 ,,,,-1 ,-1 ,-1 , 0 , 0 , 0 , 0 , 0
Multiple Barrel Culv=2,9.2,10,42,.014,.5,1,8,2,41.1,41.1, 3,Culvert #1  , 0 ,5.045
  393.34  393.34     404     404  414.66  414.66
Culvert Bottom n=.014
BC Design=,, 0 ,, 0 ,,,,,,

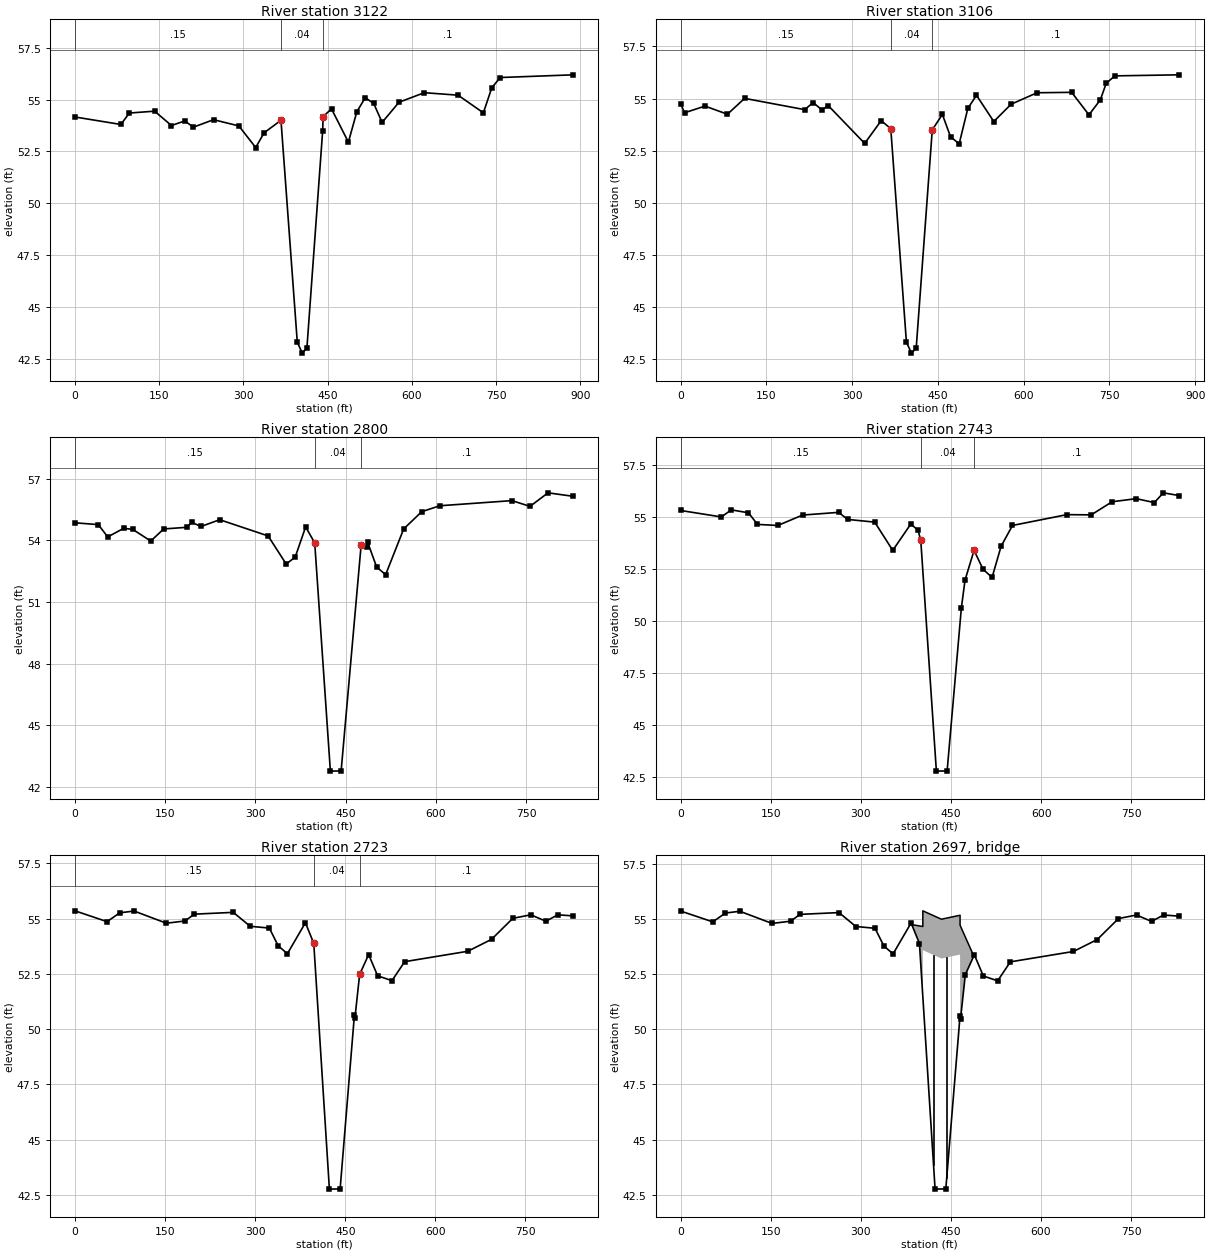
Type RM Length L Ch R = 1 ,3122    ,16.04,16.06,19.41
BEGIN DESCRIPTION:
Surveyed cross-section 3106/XS2
END DESCRIPTION:
XS GIS Cut Line= 4
     3086850.735     13807586.11     3087208.951     13807595.46
     3087308.433     13807594.31     3087737.307      13807618.6
#Sta/Elev= 30
       0   54.16   81.79    53.8    96.8   54.35  141.81   54.44  171.82   53.75
  195.54   53.97  210.95   53.67  246.85   54.03  291.86   53.73  321.87   52.69
  336.88    53.4  366.89      54  395.92   43.32  404.72   42.79  413.05   43.03
  441.14    53.5  441.89   54.18  456.89   54.55  486.94   52.95  501.96   54.41
  516.99   55.09  532.01   54.81  547.04    53.9  577.08   54.87  622.16   55.33
  682.25   55.21  727.32   54.36  742.35   55.57  757.37   56.06  887.39   56.19
#Mann= 3 , 0 , 0
       0     .15       0  366.89     .04       0  441.89      .1       0
#XS Ineff= 2 , 0
       0     312             777       0
Permanent Ineff=
       T       T
Bank Sta=366.89,441.89
XS Rating Curve= 0
Exp/Cntr=.5,.3

Type RM Length L Ch R = 1 ,3106    ,300.46,306.04,303.28
BEGIN DESCRIPTION:
Surveyed cross-section/XS1
END DESCRIPTION:
XS GIS Cut Line= 4
     3086850.669    13807602.151     3087208.885    13807611.501
     3087308.367    13807610.352     3087718.495    13807665.561
#Sta/Elev= 30
       0   54.75    6.83   54.32   42.61   54.64   81.86   54.25  111.87   55.01
   216.9   54.47  231.91   54.81  246.92   54.46  258.31   54.66  321.94   52.85
  350.75   53.94  367.56   53.56  394.92   43.32  403.72   42.79  412.05   43.03
  440.14    53.5  457.83   54.24  472.09   53.17  487.22   52.83  502.36   54.53
  517.49   55.16  547.76    53.9  578.03   54.73  623.44   55.28  683.98    55.3
  714.25   54.22  734.15   54.94  744.52   55.74  759.66   56.09  871.65   56.14
#Mann= 3 , 0 , 0
       0     .15       0  367.56     .04       0  440.14      .1       0
#XS Ineff= 2 , 0
       0     312             776       0
Permanent Ineff=
       T       T
Bank Sta=367.56,440.14
XS Rating Curve= 0
Exp/Cntr=.3,.1

Type RM Length L Ch R = 1 ,2800    ,57.01,56.94,57.02
BEGIN DESCRIPTION:
Surveyed cross-section 2628
END DESCRIPTION:
XS GIS Cut Line= 4
      3086806.56     13807899.17     3087190.439     13807911.69
     3087290.931     13807919.11     3087634.401     13807920.75
#Sta/Elev= 30
       0   54.86    38.9   54.77   54.41   54.17   80.98   54.59   95.99   54.54
  126.01   53.97   147.5   54.56  186.04   54.64  194.04   54.88  209.55   54.68
  240.58   55.01  321.11   54.22  351.13   52.85  366.13   53.19  383.45   54.66
  398.56   53.88  424.58   42.76  442.46   42.77  475.65   53.76  484.85   53.67
  486.42   53.92  501.42   52.71  516.42   52.33  546.42   54.56  576.42    55.4
  606.42   55.69  726.42   55.94  756.42   55.66  786.42   56.32  828.32   56.15
#Mann= 3 , 0 , 0
       0     .15       0  398.56     .04       0  475.65      .1       0
#XS Ineff= 2 , 0
       0     333             737       0
Permanent Ineff=
       T       T
Bank Sta=398.56,475.65
XS Rating Curve= 0
Exp/Cntr=.3,.1

Type RM Length L Ch R = 1 ,2743    ,20,19.98,20
BEGIN DESCRIPTION:
Surveyed cross-section 2628/XS4
END DESCRIPTION:
XS GIS Cut Line= 4
       3086804.7     13807956.14     3087189.511     13807968.69
     3087290.003     13807976.11     3087633.462     13807977.75
#Sta/Elev= 30
       0    55.3   67.84   54.99   84.23   55.33  112.86   55.19  127.87   54.63
   161.8   54.58  202.91   55.08  262.94   55.21  277.95   54.87  322.97   54.74
  352.99   53.38     383   54.65  394.95   54.35  399.56   53.88  425.58   42.76
  443.46   42.77  467.18   50.62  473.24   51.95  488.28   53.38  503.28   52.47
  518.28   52.08  533.28   53.58  552.21   54.58  642.64    55.1  683.28   55.09
     718   55.72  758.28   55.87  788.28   55.68  803.28   56.15  829.24   56.02
#Mann= 3 , 0 , 0
       0     .15       0  399.56     .04       0  488.28      .1       0
#XS Ineff= 2 , 0
       0     333             698       0
Permanent Ineff=
       T       T
Bank Sta=399.56,488.28
XS Rating Curve= 0
Exp/Cntr=.5,.3

Type RM Length L Ch R = 1 ,2723    ,52.03,51.63,52.42
BEGIN DESCRIPTION:
Surveyed cross-section 2628/XS3
END DESCRIPTION:
XS GIS Cut Line= 4
      3086804.05     13807976.13     3087189.185     13807988.69
     3087289.677     13807996.11     3087633.132     13807997.74
#Sta/Elev= 30
       0   55.35   53.48   54.86   74.55   55.26    98.5   55.34  152.12   54.79
  183.15   54.89  198.66    55.2  263.59   55.28  291.74   54.65  323.62   54.57
  338.29   53.77  353.64   53.41  383.65   54.81  397.56   53.88  423.58   42.76
  441.46   42.77  465.18   50.62     466   50.48   473.9   52.47  488.93   53.37
  503.93   52.41  527.74   52.19  548.93   53.05  653.93   53.52  693.52   54.06
  728.93   55.01  758.93   55.17  783.95   54.88  803.93   55.17  829.56   55.12
#Mann= 3 , 0 , 0
       0     .15       0  397.56     .04       0   473.9      .1       0
#XS Ineff= 2 , 0
       0     333             683       0
Permanent Ineff=
       T       T
Bank Sta=397.56,473.9
XS Rating Curve= 0
Exp/Cntr=.5,.3

Type RM Length L Ch R = 3 ,2697    ,,,
BEGIN DESCRIPTION:
wood foot bridge, @ Wigton, d.s. of Cheena
Bridge location found from HEC2 file and DOQQ.
0 skew
62' long from Pate
10' wide from HEC-2
2 sets of piers; assume circular; Pate info shows 1.0 width with 3 even spaces.
END DESCRIPTION:
Bridge Culvert--1,0,-1,-1, 0
Deck Dist Width WeirC Skew NumUp NumDn MinLoCord MaxHiCord MaxSubmerge Is_Ogee
20.815,10,2.6,0, 7, 7, , , .95, 0, 0,0,,
  383.63  403.17  403.17  434.17  465.17  465.17  487.76
   54.74   54.65   55.36   54.98   55.16   54.71   53.33
       0       0   53.58    53.2   53.38       0       0
  383.38  403.17  403.17  434.17  465.17  465.17  488.66
   54.78   54.65   55.36   54.98   55.16   54.71   53.74
       0       0   53.58    53.2   53.38       0       0
Pier Skew, UpSta & Num, DnSta & Num=  ,420.99, 2 ,420.99, 2 , 0 , 0 , 0 ,,
       1       1
       0     100
       1       1
       0     100
Pier Skew, UpSta & Num, DnSta & Num=  ,442.99, 2 ,442.99, 2 , 0 , 0 , 0 ,,
       1       1
       0     100
       1       1
       0     100
BR Coef=-1 , 1 , 1 ,1.05, 0 ,,,.8,-1,1.2,0,
WSPro=,,,, 1 ,,,, 0 ,,,, 0 ,,,,-1 ,-1 ,-1 , 0 , 0 , 0 , 0 , 0
BC Design=,, 0 ,, 0 ,,,,,,

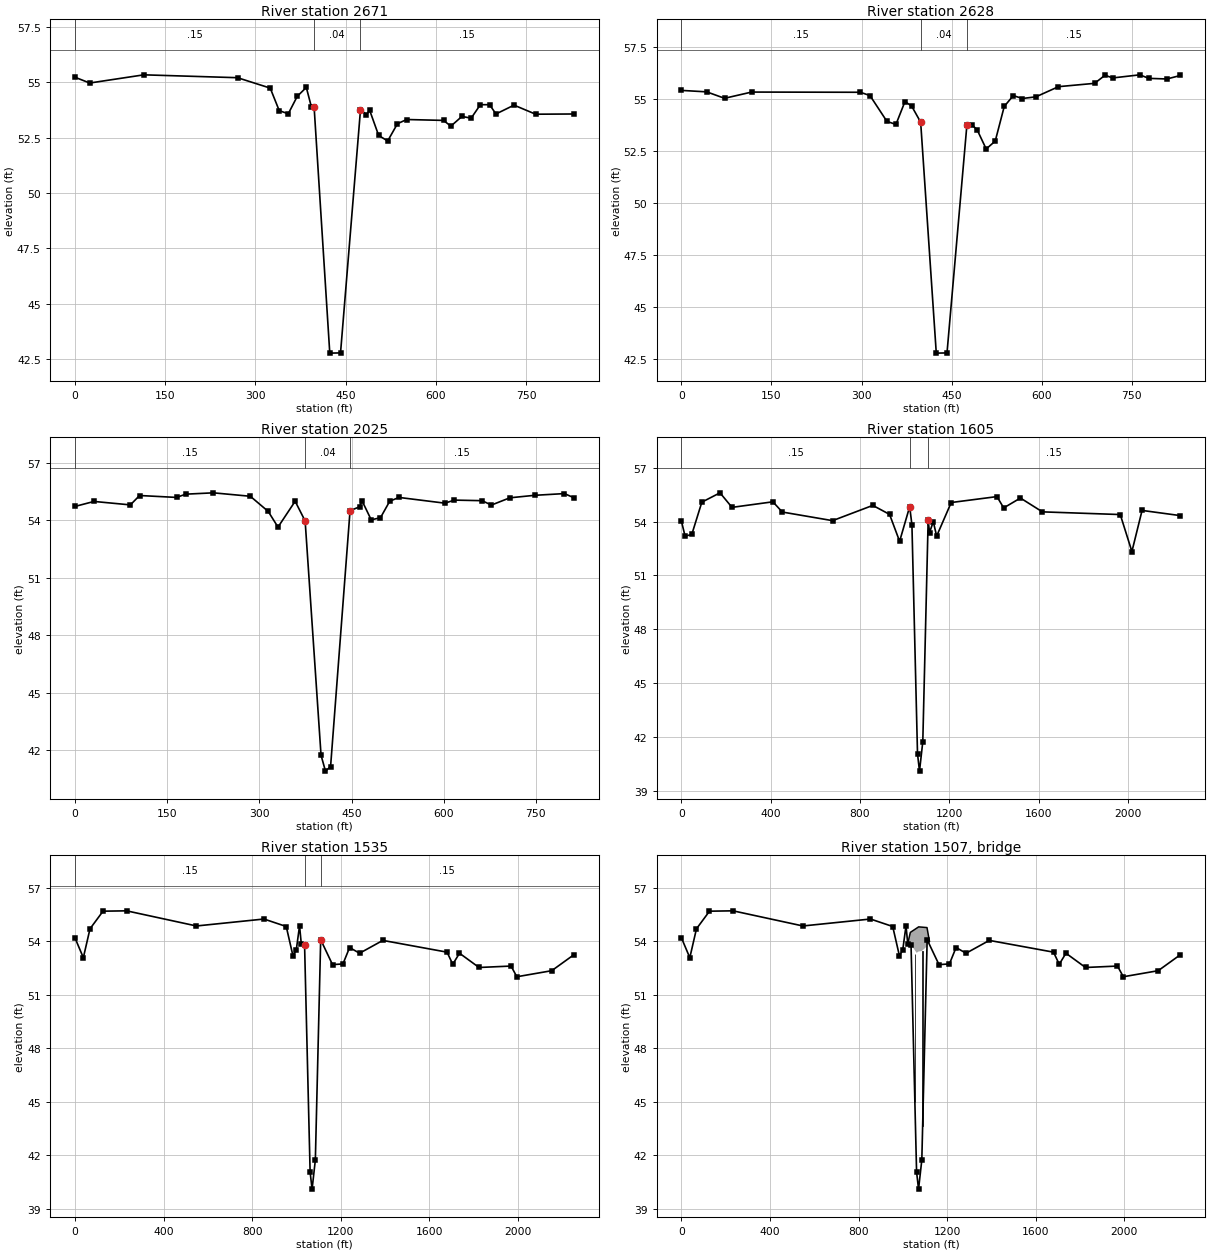
Type RM Length L Ch R = 1 ,2671    ,42.24,43.49,46.9
BEGIN DESCRIPTION:
Surveyed cross-section 2628/XS2
END DESCRIPTION:
XS GIS Cut Line= 4
      3086802.99     13808033.12     3087186.744     13808040.26
     3087287.236     13808047.68     3087632.192     13808054.74
#Sta/Elev= 30
       0   55.23   24.51   54.97  114.53   55.34   270.2   55.21  324.57   54.74
  339.57   53.72  354.57   53.58  369.57   54.37  384.58   54.77  393.04   53.89
  397.56   53.88  423.58   42.76  441.46   42.77  474.65   53.76  484.59   53.54
  489.85   53.74  504.85    52.6  519.86   52.35  536.09   53.13  551.41   53.32
  612.68   53.28  624.88   53.02  643.31   53.46  658.63   53.38  673.94   53.99
  689.26   53.99   699.9   53.57   729.9   53.97  765.84   53.56  829.61   53.57
#Mann= 3 , 0 , 0
       0     .15       0  397.56     .04       0  474.65     .15       0
#XS Ineff= 2 , 0
       0     332             636       0
Permanent Ineff=
       T       T
Bank Sta=397.56,474.65
XS Rating Curve= 0
Exp/Cntr=.5,.3

Type RM Length L Ch R = 1 ,2628    ,596.06,602.81,606.17
BEGIN DESCRIPTION:
Surveyed cross-section/XS1
END DESCRIPTION:
XS GIS Cut Line= 4
     3086800.822    13808060.192     3087183.555    13808083.611
     3087284.047    13808091.031     3087630.041    13808120.378
#Sta/Elev= 30
       0   55.41   42.01   55.34   71.81   55.03   116.9   55.33  298.14   55.32
  314.14   55.16  342.32   53.92  357.35   53.77  372.37   54.87  383.45   54.66
  398.56   53.88  424.58   42.76  442.46   42.77  475.65   53.76  484.21   53.75
   492.7   53.51  507.75   52.59  522.81   52.97  537.86   54.64  552.91   55.16
  567.97   55.02  590.57    55.1  628.18   55.59   688.4   55.75  705.71   56.14
  718.51   56.01  763.67   56.16  778.72   55.99  808.83   55.96  831.45   56.13
#Mann= 3 , 0 , 0
       0     .15       0  398.56     .04       0  475.65     .15       0
#XS Ineff= 2 , 0
       0     333             594       0
Permanent Ineff=
       T       T
Bank Sta=398.56,475.65
XS Rating Curve= 0
Exp/Cntr=.3,.1

Type RM Length L Ch R = 1 ,2025    ,422.24,419.62,415.49
BEGIN DESCRIPTION:
Surveyed cross-section
END DESCRIPTION:
XS GIS Cut Line= 4
     3086797.478    13808662.045     3087155.377    13808678.594
      3087258.65    13808697.027     3087606.636     13808722.23
#Sta/Elev= 30
       0   54.73   31.03   54.99   90.12   54.81  105.13    55.3   165.2    55.2
  180.21   55.37  225.26   55.44  285.33   55.26  314.43   54.47  330.37   53.65
  358.28      55  374.54   53.97  400.42   41.74  407.62   40.91  415.95   41.15
  447.63   54.51  463.19   54.71  467.05   55.03  482.09   54.03  497.13   54.14
  512.16      55   527.2    55.2  601.95    54.9  617.44   55.06  662.56   55.03
   677.6    54.8  707.68   55.18  747.87   55.31  796.51    55.4  812.08   55.18
#Mann= 3 , 0 , 0
       0     .15       0  374.54     .04       0  447.63     .15       0
#XS Ineff= 2 , 0
       0     315             524       0
Permanent Ineff=
       T       T
Bank Sta=374.54,447.63
XS Rating Curve= 0
Exp/Cntr=.3,.1

Type RM Length L Ch R = 1 ,1605    ,70.01,70.31,70.01
BEGIN DESCRIPTION:
Surveyed cross-section 1414/XS4
END DESCRIPTION:
XS GIS Cut Line= 5
     3086121.303    13809050.216     3087135.824    13809100.472
     3087230.528     13809113.38     3087781.645     13809137.82
     3088347.465     13809049.29
#Sta/Elev= 30
       0   54.01   16.22   53.19   46.25   53.28   91.31   55.08  172.67    55.6
  226.47   54.79  409.68    55.1  451.75   54.53  677.03   54.05  857.25    54.9
  932.34    54.4  977.39    52.9  1022.5   54.83 1032.56   53.82 1057.61   41.06
 1066.51    40.1 1081.26   41.74 1105.34    54.1 1111.34   53.39 1128.33   53.99
 1143.35   53.19  1208.6   55.06 1413.61   55.39 1443.64   54.76 1518.72   55.31
  1617.1   54.54 1965.98   54.39 2018.13   52.33 2063.67   54.62 2235.71   54.33
#Mann= 3 , 0 , 0
       0     .15       0  1022.5     .04       0 1105.34     .15       0
#XS Ineff= 2 , 0
       0     950            1192       0
Permanent Ineff=
       T       T
Bank Sta=1022.5,1105.34
XS Rating Curve= 0
Exp/Cntr=.5,.3

Type RM Length L Ch R = 1 ,1535    ,56.47,56.26,56.1
BEGIN DESCRIPTION:
Surveyed cross-section 1414/XS3
END DESCRIPTION:
XS GIS Cut Line= 5
     3086114.849    13809119.996      3087129.37    13809170.252
     3087224.074     13809183.16     3087785.544     13809208.06
     3088358.285     13809118.45
#Sta/Elev= 30
       0    54.2    37.7   53.09   67.73   54.71  126.56    55.7  232.94   55.72
  548.32   54.87  853.42   55.26  953.82   54.84  983.86   53.21  998.87    53.5
 1013.89   54.88 1021.89   53.85 1036.56   53.82 1061.61   41.06 1070.51    40.1
 1085.26   41.74 1109.34    54.1 1162.76    52.7 1209.89   52.74  1239.9   53.66
 1284.94   53.34 1390.04   54.06 1679.94    53.4 1705.71   52.72 1736.08   53.34
 1824.36   52.54 1968.77   52.62 1995.03   52.02 2152.57   52.36 2253.08   53.26
#Mann= 3 , 0 , 0
       0     .15       0 1036.56     .04       0 1109.34     .15       0
#XS Ineff= 2 , 0
       0     955            1198       0
Permanent Ineff=
       T       T
Bank Sta=1036.56,1109.34
XS Rating Curve= 0
Exp/Cntr=.5,.3

Type RM Length L Ch R = 3 ,1507    ,,,
BEGIN DESCRIPTION:
Rutherglenn Bridge
Roadway profile from LIDAR, bridge elevations from Pate.
0 skew
46' width from DOQQ
75' length from Pate
2 sets of circular piers (Pate) 24" dia; spacing of piers from picture.
redo alk 2/9/00
END DESCRIPTION:
Bridge Culvert--1,0,-1,-1, 0
Deck Dist Width WeirC Skew NumUp NumDn MinLoCord MaxHiCord MaxSubmerge Is_Ogee
5.13,46,2.6,0, 5, 5, , , .95, 0, 0,0,,
 1021.81 1033.42 1070.92 1108.62 1119.72
   53.89   54.51   54.82   54.78   54.01
           53.13   53.44    53.5
 1034.16 1035.42 1072.92 1110.62 1125.51
   54.38   54.51   54.82   54.78   53.85
           53.13   53.44    53.5
Pier Skew, UpSta & Num, DnSta & Num=  ,1053.92, 2 ,1055.92, 2 , 0 , 0 , 0 ,,
       2       2
       0     100
       2       2
       0     100
Pier Skew, UpSta & Num, DnSta & Num=  ,1088.92, 2 ,1090.92, 2 , 0 , 0 , 0 ,,
       2       2
       0     100
       2       2
       0     100
BR Coef=-1 , 1 , 1 ,1.05, 0 ,,,.8,-1,1.2,0,
WSPro=,,,, 1 ,,,, 0 ,,,, 0 ,,,,-1 ,-1 ,-1 , 0 , 0 , 0 , 0 , 0
BC Design=,, 0 ,, 0 ,,,,,,

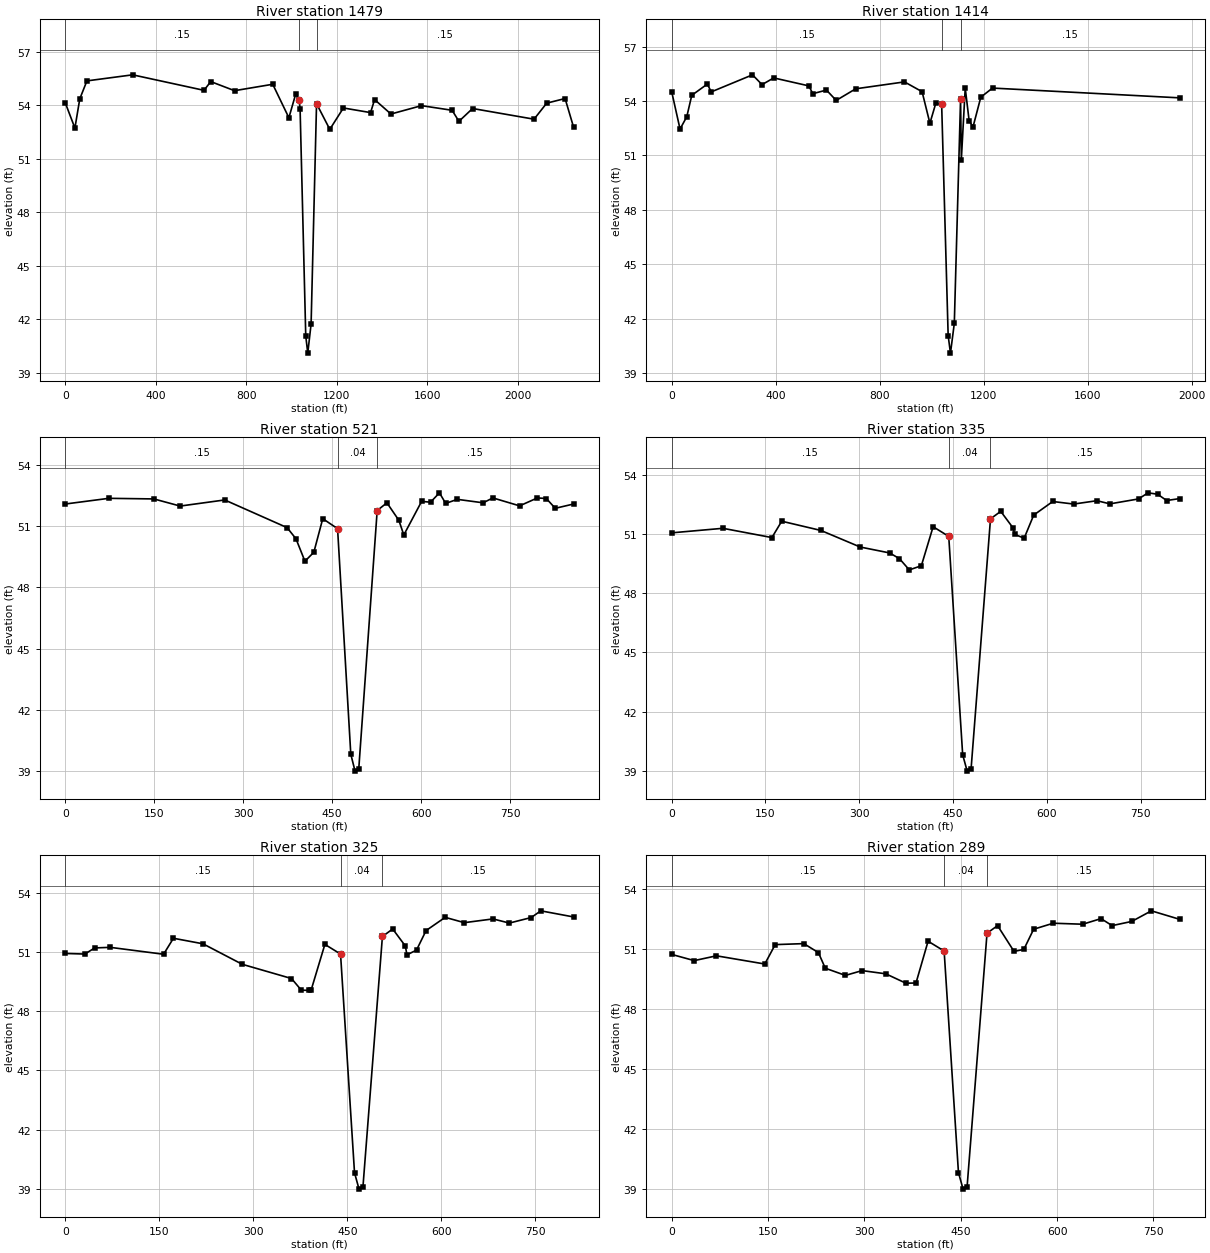
Type RM Length L Ch R = 1 ,1479    ,65.53,64.94,61.33
BEGIN DESCRIPTION:
Surveyed cross-section 1414/XS2
END DESCRIPTION:
XS GIS Cut Line= 5
     3086109.685    13809175.826     3087124.206    13809226.082
      3087218.91     13809238.99     3087787.505      13809264.2
      3088350.96    13809199.591
#Sta/Elev= 30
       0   54.16   42.87   52.73   64.41   54.37   96.01   55.38  298.18   55.72
  613.57   54.85   643.6   55.34  748.73   54.83  917.67   55.19  989.03   53.31
 1019.09   54.64 1034.23   54.33 1038.56   53.82 1063.61   41.06 1072.51    40.1
 1087.26   41.74 1111.34    54.1 1169.99   52.66 1230.05   53.86 1350.17    53.6
 1368.05   54.33 1440.26   53.52 1575.39   53.99 1710.69   53.73 1740.89   53.11
 1801.28   53.83 2073.05   53.23 2129.02   54.13 2210.29   54.39 2247.65   52.79
#Mann= 3 , 0 , 0
       0     .15       0 1034.23     .04       0 1111.34     .15       0
#XS Ineff= 2 , 0
       0     960            1199       0
Permanent Ineff=
       T       T
Bank Sta=1034.23,1111.34
XS Rating Curve= 0
Exp/Cntr=.5,.3

Type RM Length L Ch R = 1 ,1414    ,916.45,892.38,926.93
BEGIN DESCRIPTION:
Surveyed cross-section/XS1
END DESCRIPTION:
XS GIS Cut Line= 4
     3086105.348    13809240.492     3087119.869    13809290.748
     3087214.573    13809303.656     3088058.671    13809296.826
#Sta/Elev= 30
       0   54.51   32.19   52.45   58.09   53.13   77.25   54.31  137.09   54.93
  152.34    54.5  310.91   55.44  347.58    54.9  392.63   55.27   527.8   54.83
  542.82    54.4  595.33    54.6  632.93   54.03  708.02   54.67  895.55   55.05
  963.33   54.51  993.37   52.77 1015.77   53.86 1038.56   53.82 1063.61   41.06
 1072.51    40.1 1087.26   41.74 1111.34    54.1 1114.27   50.76 1129.27   54.71
 1144.27   52.91 1159.27   52.57 1189.27   54.21 1234.28   54.71 1955.47   54.17
#Mann= 3 , 0 , 0
       0     .15       0 1038.56     .04       0 1111.34     .15       0
#XS Ineff= 2 , 0
       0     964            1196       0
Permanent Ineff=
       T       T
Bank Sta=1038.56,1111.34
XS Rating Curve= 0
Exp/Cntr=.3,.1

Type RM Length L Ch R = 1 ,521     ,125.91,186.71,225.3
BEGIN DESCRIPTION:
Surveyed cross-section
END DESCRIPTION:
XS GIS Cut Line= 4
     3086649.019    13810154.772     3087084.138    13810179.594
     3087189.044    13810198.186     3087503.295    13810213.449
#Sta/Elev= 30
       0    52.1    73.6   52.38  149.51   52.35   193.8      52  268.92    52.3
  374.09   50.94  389.11   50.39  404.14   49.29  419.16   49.73  434.19   51.38
  459.18   50.89  481.47   39.81  488.67   38.98  494.86   39.07  525.97   51.78
  542.37   52.16  562.51    51.3  570.86   50.58  600.89   52.23  615.91   52.19
  630.93   52.65  641.43   52.13  660.96   52.33  704.57   52.16  721.03    52.4
  766.09   52.01  796.12    52.4  811.14   52.37  826.16   51.89  856.99    52.1
#Mann= 3 , 0 , 0
       0     .15       0  459.18     .04       0  525.97     .15       0
#XS Ineff= 2 , 0
       0     402             614       0
Permanent Ineff=
       T       T
Bank Sta=459.18,525.97
XS Rating Curve= 0
Exp/Cntr=.3,.1

Type RM Length L Ch R = 1 ,335     ,10.16,10.08,10.55
BEGIN DESCRIPTION:
Surveyed cross-section 521
END DESCRIPTION:
XS GIS Cut Line= 4
     3086674.268    13810243.473     3087068.608     13810364.86
     3087173.513    13810383.452     3087462.808    13810435.579
#Sta/Elev= 30
       0   51.07   81.94    51.3  160.33   50.83  176.02   51.66   238.8   51.19
  301.58   50.35  348.66   50.05  364.36   49.76  380.05   49.19  399.38    49.4
  418.19   51.38  443.18   50.89  465.47   39.81  472.67   38.98  478.86   39.07
  509.97   51.78  526.37   52.16  546.51    51.3  548.59   50.99  563.84    50.8
  579.08   51.97  609.56   52.66  643.01   52.53  680.19    52.7  701.01   52.54
  746.73   52.79  761.98    53.1  777.22   53.03  791.74   52.71  813.09   52.81
#Mann= 3 , 0 , 0
       0     .15       0  443.18     .04       0  509.97     .15       0
#XS Ineff= 2 , 0
       0     387             604       0
Permanent Ineff=
       T       T
Bank Sta=443.18,509.97
XS Rating Curve= 0
Exp/Cntr=.3,.1

Type RM Length L Ch R = 1 ,325     ,35.55,35.26,37.86
BEGIN DESCRIPTION:
Surveyed cross-section 521/XS4
END DESCRIPTION:
XS GIS Cut Line= 4
     3086677.533    13810254.942     3087066.258      13810374.6
     3087171.163    13810393.192     3087463.902    13810446.521
#Sta/Elev= 30
       0   50.92   31.35   50.89   47.05    51.2   71.66   51.23  156.91   50.88
  172.61   51.69  219.69   51.41  282.47   50.37  360.94   49.65  376.64   49.06
   389.1   49.05  392.33   49.07  414.19   51.38  439.18   50.89  461.47   39.81
  468.67   38.98  474.86   39.07  505.97   51.78  522.37   52.16  542.51    51.3
  545.12   50.85  560.36   51.09  575.61   52.08   606.1   52.75   636.6   52.48
  682.34   52.67  708.43   52.46  743.33   52.74  758.57   53.08  810.82   52.77
#Mann= 3 , 0 , 0
       0     .15       0  439.18     .04       0  505.97     .15       0
#XS Ineff= 2 , 0
       0     383             602       0
Permanent Ineff=
       T       T
Bank Sta=439.18,505.97
XS Rating Curve= 0
Exp/Cntr=.5,.3

Type RM Length L Ch R = 1 ,289     ,179.45,175.3,224.49
BEGIN DESCRIPTION:
Surveyed cross-section 521/XS3
END DESCRIPTION:
XS GIS Cut Line= 4
     3086688.959    13810295.081     3087058.029     13810408.69
     3087162.934    13810427.282     3087456.243    13810483.725
#Sta/Elev= 30
       0   50.72   35.09   50.41   69.72   50.65  144.96   50.24  161.18   51.21
  205.77   51.26  228.44   50.81  239.12   50.03  270.51   49.67  296.46   49.91
  333.29   49.75  364.68   49.28  380.38   49.29  399.19   51.38  424.18   50.89
  446.47   39.81  453.67   38.98  459.86   39.07  490.97   51.78  507.37   52.16
  532.99   50.87  548.27   50.97  563.54   51.98  594.09   52.28  639.92   52.23
  668.42   52.51  685.74   52.16  716.29   52.37  746.84    52.9  791.39   52.47
#Mann= 3 , 0 , 0
       0     .15       0  424.18     .04       0  490.97     .15       0
#XS Ineff= 2 , 0
       0     370             593       0
Permanent Ineff=
       T       T
Bank Sta=424.18,490.97
XS Rating Curve= 0
Exp/Cntr=.5,.3

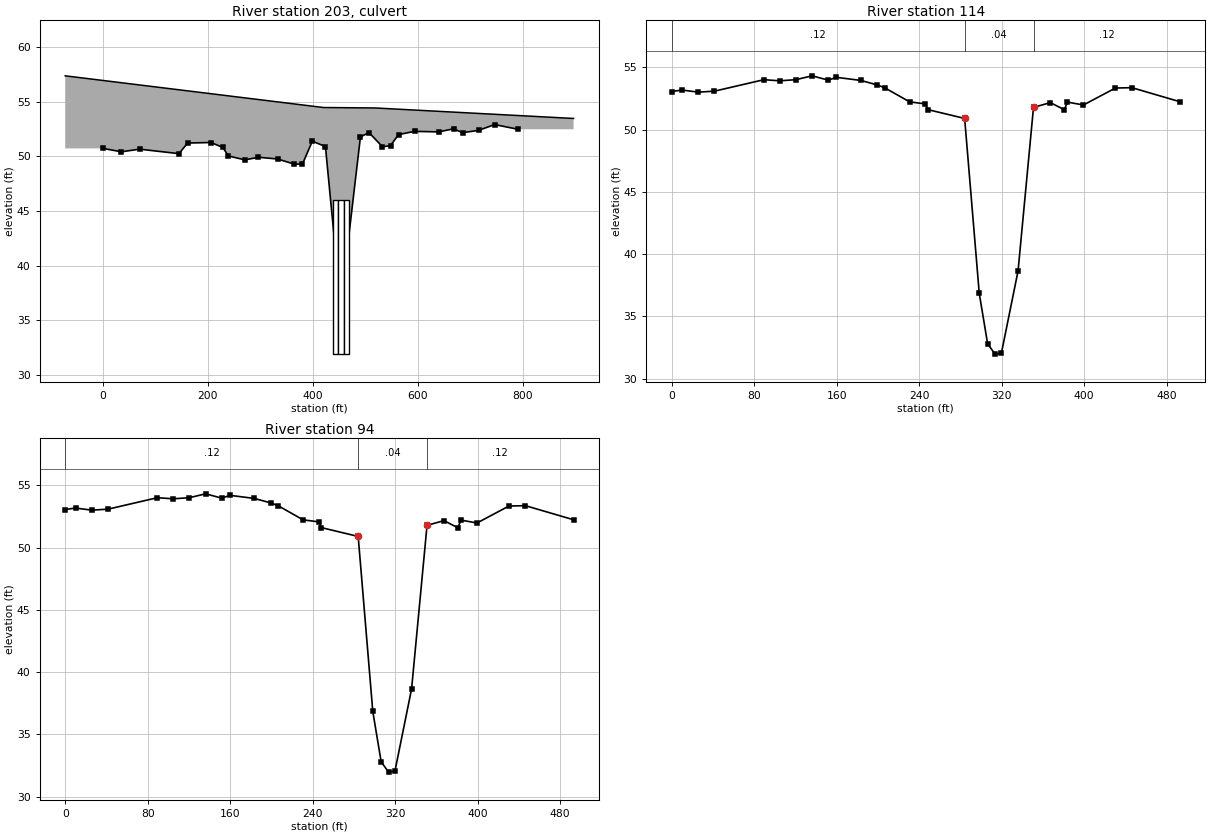
Type RM Length L Ch R = 2 ,203     ,,,
BEGIN DESCRIPTION:
Braeswood Culvert.  Top-of-Road is coded from survey and additional field measurements and observations.
END DESCRIPTION:
Bridge Culvert--1,0,-1,-1, 0
Deck Dist Width WeirC Skew NumUp NumDn MinLoCord MaxHiCord MaxSubmerge Is_Ogee
37.65,100,2.6,0, 7, 7, , , .95, 0, 0,0,,
  -72.06  420.64  420.74  469.74  518.74  518.84  897.31
   57.36   54.46   54.46   54.44   54.42   54.42   53.46
                                                        
 -212.06  280.64  280.74  329.74  378.74  378.84  757.31
   57.36   54.46   54.46   54.44   54.42   54.42   53.46
                                                        
BR Coef=-1 , 0 , 0 ,, 0 ,,,.8,-1,,0,
WSPro=,,,, 1 ,,,, 0 ,,,, 0 ,,,,-1 ,-1 ,-1 , 0 , 0 , 0 , 0 , 0
Multiple Barrel Culv=2,14.1,10,164,.014,.5,1,8,2,31.9,31.9, 3,Culvert #1  , 0 ,5.65
  442.84  302.84  453.67  313.67   464.5   324.5
Culvert Bottom n=.014
BC Design=,, 0 ,, 0 ,,,,,,

Type RM Length L Ch R = 1 ,114     ,20,20,20
BEGIN DESCRIPTION:
Surveyed cross-section 521/XS2
END DESCRIPTION:
XS GIS Cut Line= 4
       3086824.2      13810491.3       3087041.8      13810562.2
        3087146.      13810580.7       3087298.2      13810619.7
#Sta/Elev= 30
       0   53.05    9.99   53.17   25.77      53   41.54   53.08   89.46      54
  104.65   53.91  120.42      54  136.25   54.31  151.98   53.96  159.65   54.19
  183.53   53.94   199.3   53.58  206.45   53.36  230.83   52.22  246.07   52.06
  248.43    51.6  284.18   50.89  298.35   36.85  306.47   32.81  313.67   31.98
  319.86   32.07  335.99   38.66  350.97   51.78  367.37   52.16  380.84   51.59
  383.94    52.2  399.43   51.97   430.4   53.33  446.38   53.36  493.07   52.23
#Mann= 3 , 0 , 0
       0     .12       0  284.18     .04       0  350.97     .12       0
#XS Ineff= 2 , 0
       0     230             489       0
Permanent Ineff=
       T       T
Bank Sta=284.18,350.97
XS Rating Curve= 0
Exp/Cntr=.5,.3

Type RM Length L Ch R = 1 ,94      ,0,0,0
BEGIN DESCRIPTION:
Surveyed cross-section 521/XS2
END DESCRIPTION:
XS GIS Cut Line= 4
        3086818.      13810510.4       3087066.4      13810586.9
       3087165.5      13810606.3       3087293.2      13810639.1
#Sta/Elev= 30
       0   53.05    9.99   53.17   25.77      53   41.54   53.08   89.46      54
  104.65   53.91  120.42      54  136.25   54.31  151.98   53.96  159.65   54.19
  183.53   53.94   199.3   53.58  206.45   53.36  230.83   52.22  246.07   52.06
  248.43    51.6  284.18   50.89  298.35   36.85  306.47   32.81  313.67   31.98
  319.86   32.07  335.99   38.66  350.97   51.78  367.37   52.16  380.84   51.59
  383.94    52.2  399.43   51.97   430.4   53.33  446.38   53.36  493.07   52.23
#Mann= 3 , 0 , 0
       0     .12       0  284.18     .04       0  350.97     .12       0
#XS Ineff= 2 , 0
       0     230             489       0
Permanent Ineff=
       T       T
Bank Sta=284.18,350.97
XS Rating Curve= 0
Exp/Cntr=.3,.1

Chan Stop Cuts=-1